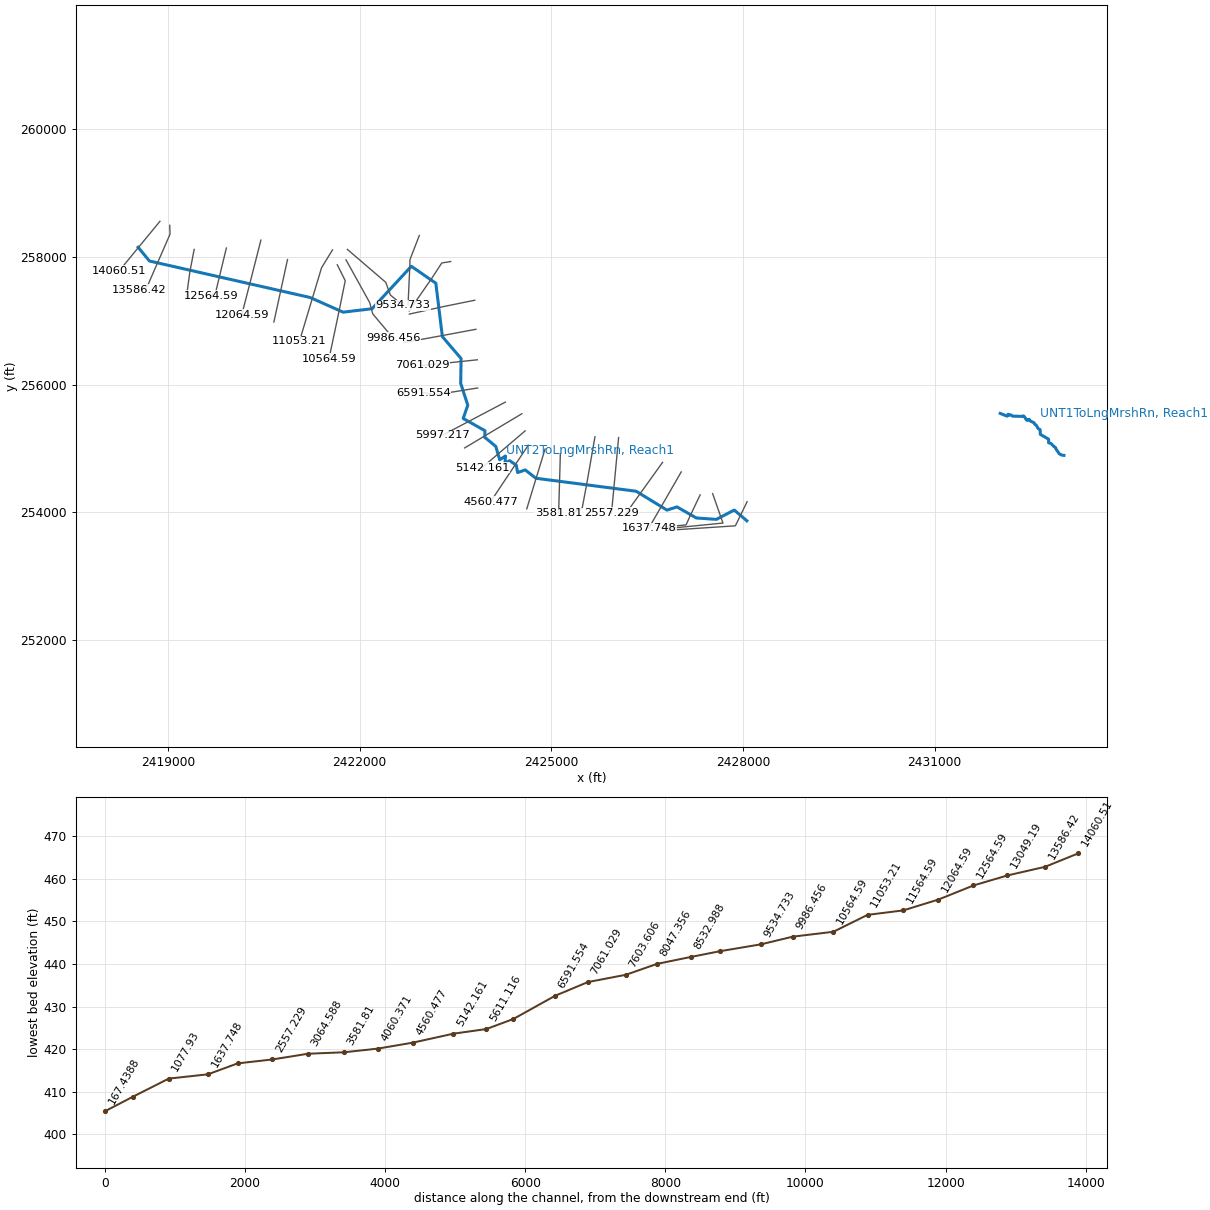
--- LongMarshRun.prj (project) ---

Proj Title=Long Marsh Run
Current Plan=p01
Default Exp/Contr=0.3,0.1
English Units
Geom File=g01
Flow File=f01
Plan File=p01
Y Axis Title=Elevation
X Axis Title(PF)=Main Channel Distance
X Axis Title(XS)=Station
BEGIN DESCRIPTION:
END DESCRIPTION:
DSS Export Rating Curves= 0
DSS Export Rating Curve Sorted= 0
DSS Export Volume Flow Curves= 0
DXF OffsetX= 0
DXF OffsetY= 0
DXF ScaleX= 1
DXF ScaleY= 10

--- LongMarshRun.p01 (plan) ---

Plan Title=LongMarshRun
Program Version=4.10
Short Identifier=LMR
Geom File=g01
Flow File=f01
Subcritical Flow
K Sum by GR= 0
Std Step Tol= 0.01
Critical Tol= 0.01
Num of Std Step Trials= 20
Max Error Tol= 0.3
Flow Tol Ratio= 0.001
Split Flow NTrial= 30
Split Flow Tol= 0.02
Split Flow Ratio= 0.02
Log Output Level= 0
Friction Slope Method= 1
Unsteady Friction Slope Method= 2
Unsteady Bridges Friction Slope Method= 1
Parabolic Critical Depth
Global Vel Dist= 0 , 0 , 0
Global Log Level= 0
CheckData=True
Encroach Param=-1 ,0,0, 0
Computation Interval=1HOUR
Output Interval=1HOUR
Run HTab= 0
Run UNet= 0
Run PostProcess= 0
Run WQNet= 0
UNET Theta= 1
UNET Theta Warmup= 1
UNET ZTol= 0.02
UNET ZSATol= 0.05
UNET MxIter= 20
UNET MaxInSteps= 0
UNET DtIC= 0
UNET DtMin= 0
UNET MaxCRTS= 20
UNET WFStab= 2
UNET SFStab= 1
UNET WFX= 1
UNET SFX= 1
UNET DSS MLevel= 4
UNET DZMax Abort= 100
UNET Convert EG Bridges= 0
UNET Use Existing IB Tables=-1
UNET Froude Reduction=False
UNET Froude Limit= 1
UNET Froude Power= 10
UNET Time Slicing=0,0, 5
UNET Junction Losses=0
Instantaneous Interval=1HOUR
Write IC File= 0
Write IC File at Sim End=0
Echo Input=False
Echo Parameters=False
Echo Output=False
Write Detailed= 0
WQ AD Non Conservative
WQ ULTIMATE=-1
WQ Max Comp Step=1HOUR
WQ Output Interval=15MIN
WQ Output Selected Increments= 0
WQ Output face flow=0
WQ Output face velocity=0
WQ Output face area=0
WQ Output face dispersion=0
WQ Output cell volume=0
WQ Output cell surface area=0
WQ Output cell continuity=0
WQ Output cumulative cell continuity=0
WQ Output face conc=0
WQ Output face dconc_dx=0
WQ Output face courant=0
WQ Output face peclet=0
WQ Output face adv mass=0
WQ Output face disp mass=0
WQ Output cell mass=0
WQ Output cell source sink temp=0
WQ Output cell source sink nsm=0
WQ Output MaxMinRange=-1
WQ Daily Max Min Mean=-1
WQ Daily Range=0
WQ Daily Time=0
WQ Create Restart=0
WQ Fixed Restart=0
WQ System Summary=0
WQ Use Fixed Temperature=0
Sorting and Armoring Iterations= 10
XS Update Threshold= 0.02
Hydraulics Update Threshold= 0.02
Energy Slope Method= 1
Volume Change Method= 0
XS Weighting Method= 0
Number of US Weighted Cross Sections= 1
Number of DS Weighted Cross Sections= 1
Upstream XS Weight=0.25
Main XS Weight=0.5
Downstream XS Weight=0.25
Number of DS XS's Weighted with US Boundary= 1
Upstream Boundary Weight= 1
Weight of XSs Associated with US Boundary= 0
Number of US XS's Weighted with DS Boundary= 1
Downstream Boundary Weight= 0.5
Weight of XSs Associated with DS Boundary= 0.5
Sediment Output Level= 4
Mass or Volume Output= 0
Output Increment Type= 1
Profile and TS Output Increment= 10
XS Output Flag= 0
XS Output Increment= 10
Disregard all LS=0
Disregard all Conn=0
Disregard all Breaches=0
Disregard all Pumps=0

--- LongMarshRun.f01 (steady flow) ---

Flow Title=LongMarshRun
Program Version=4.10
Number of Profiles= 1
Profile Names=PF 1
River Rch & RM=LngMarshRun,Reach1          ,16474.07
    1907
River Rch & RM=LngMarshRun,Reach1          ,9035.821
    3628
River Rch & RM=LngMarshRun,Reach1          ,2013.155
    3913
River Rch & RM=UNT1ToLngMrshRn,Reach1          ,1405.171
     414
River Rch & RM=UNT2ToLngMrshRn,Reach1          ,14060.51
     793
River Rch & RM=UNT2ToLngMrshRn,Reach1          ,8941.396
    1920
Boundary for River Rch & Prof#=LngMarshRun,Reach1          , 1
Up Type= 0
Dn Type= 3
Dn Slope=0.00322
Boundary for River Rch & Prof#=UNT1ToLngMrshRn,Reach1          , 1
Up Type= 0
Dn Type= 3
Dn Slope=0.00987
Boundary for River Rch & Prof#=UNT2ToLngMrshRn,Reach1          , 1
Up Type= 0
Dn Type= 3
Dn Slope=0.0085
DSS Import GetInterval= 0
DSS Import GetPeak= 0
DSS Import FillOption= 0

--- LongMarshRun.g01 (geometry) ---

Geom Title=LongMarshRun
Program Version=4.10

River Reach=UNT2ToLngMrshRn ,Reach1
Reach XY= 30
2418531.18647894 258151.306455942418709.31145078257935.941729188
 2421223.7211201257365.038999602 2421739.5196292257135.525022939
2422193.16570352257189.1709130262422807.57523586257853.754229516
2423191.14008552 257588.835139932423293.57065494 256752.93261227
2423586.64946511256409.5064618592423580.40046185256020.126991272
2423691.51047586255679.6453887672423619.63561961255471.312144026
2423959.56604211255280.6871971942423957.13560078 255176.86752294
2424130.05224968255033.8120347712424190.81590769254825.825902194
2424281.78816669 254884.159446942424273.80229028254772.701008439
2424346.71881111254810.5480456052424450.19104511254741.451070935
2424471.71888919254625.4788619432424590.46897978254666.103780687
2424757.48275335254535.8953796922426325.79162461254332.795392185
2426809.27523769254037.4574001882426965.46882294254087.284400269
2427268.94098502 253914.367751362427581.78845644253892.145354852
2427861.94537644 254038.205430182428059.46466644253870.325516596

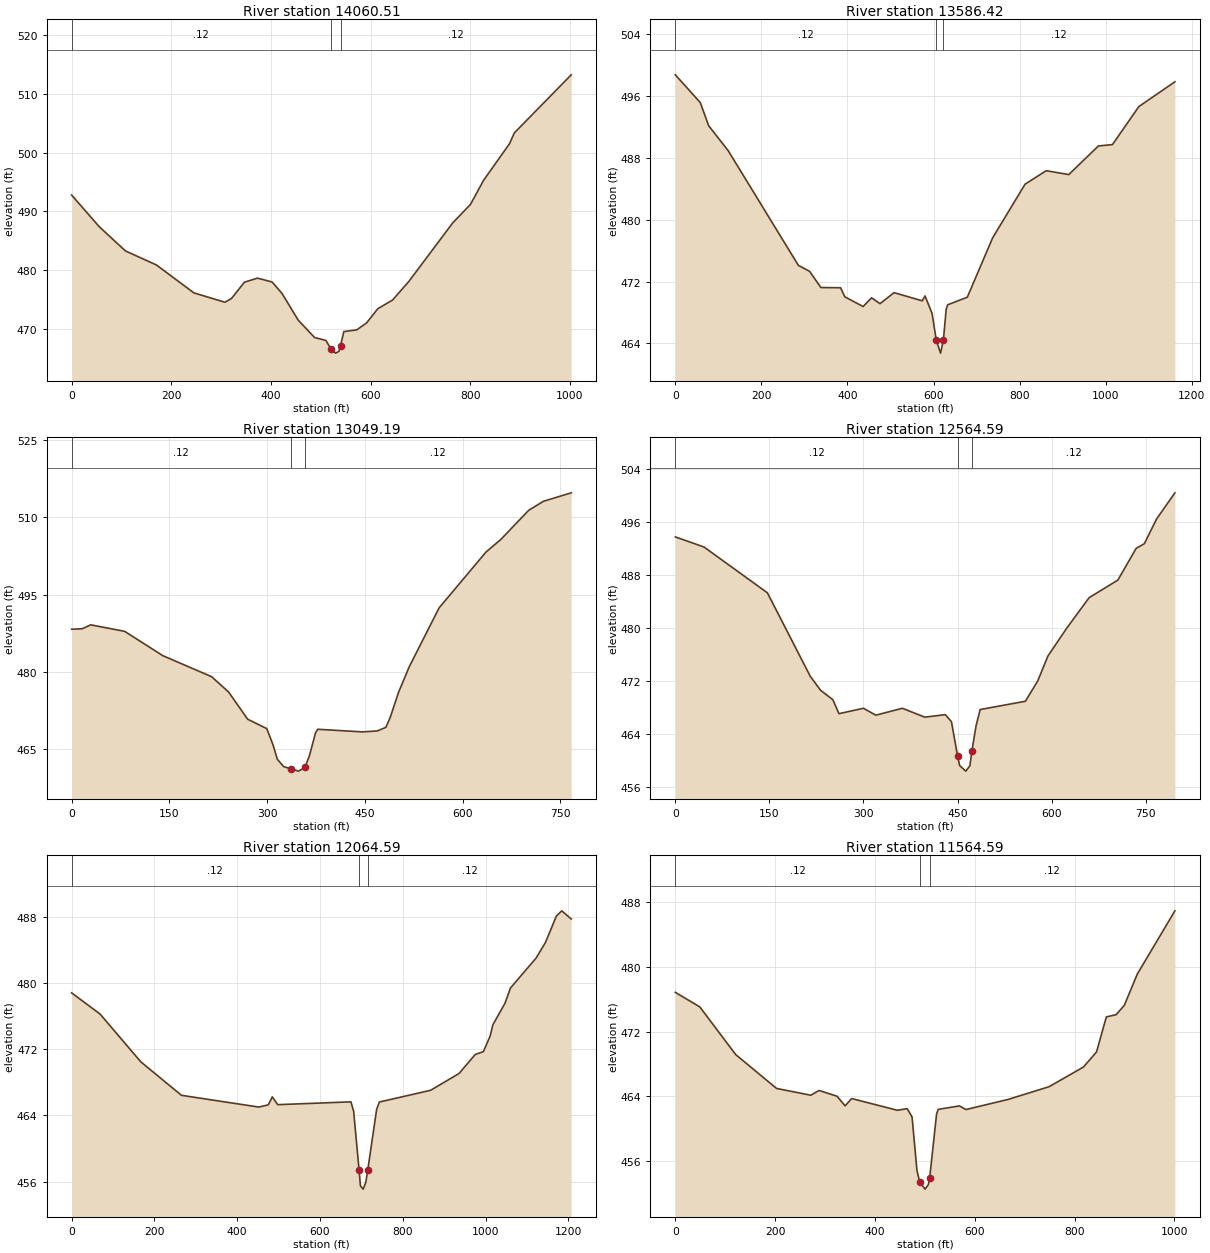
Type RM Length L Ch R = 1 ,14060.51,441.38,474.09,453.15
Node Name=1012
XS GIS Cut Line= 3
2418872.77076952258557.5966538492418554.87081477258170.938634515
2418236.08011377257783.196627855
#Sta/Elev= 30
       0  492.79   55.62  487.39  107.96  483.29  170.13   480.9  245.37  476.15
  307.54  474.56  320.62  475.18   346.8  477.97  372.97  478.66  402.42     478
  422.05  476.07  454.76  471.51  487.48  468.56  510.34  468.06  520.12  466.63
   529.9   465.9  536.42   466.2  539.68  467.16   546.2  469.56  572.27  469.86
  591.83  471.04  614.65  473.47  643.98  474.93  676.58  478.08  764.59  488.04
  800.44  491.21  826.52  495.28  878.67  501.52  888.45  503.37 1002.53  513.25
#Mann= 3 , 0 , 0
       0     .12       0  520.12    .045       0  539.68     .12       0
Bank Sta=520.12,539.68
XS Rating Curve= 0 ,0
Exp/Cntr=0.3,0.1

Type RM Length L Ch R = 1 ,13586.42,525.94,537.23,542.19
Node Name=1013
XS GIS Cut Line= 5
2419026.43155144258494.4078038482419030.62511261258355.694498599
2418860.83411361 257965.948887022418677.73014911257545.644281432
2418551.17134711257489.199512437
#Sta/Elev= 30
       0  498.77   58.09  495.17   77.46  492.18  122.64  488.97  285.93  474.11
   312.1  473.33  338.26  471.24  384.04  471.21  393.85  470.04  436.36  468.78
  455.98  469.91  475.61  469.15  508.31  470.58  573.72  469.52  580.27  470.15
  596.65  467.88  606.47   464.4   616.3  462.75  622.85  464.42  629.39   468.4
  632.67     469  678.52  469.99  737.46  477.68  812.78  484.62   861.9  486.36
  914.29  485.86  983.06  489.56 1015.81  489.74 1077.14  494.66 1160.93  497.87
#Mann= 3 , 0 , 0
       0     .12       0  606.47    .045       0  622.85     .12       0
Bank Sta=606.47,622.85
XS Rating Curve= 0 ,0
Exp/Cntr=0.3,0.1

Type RM Length L Ch R = 1 ,13049.19,481.08,484.6,476.73
Node Name=1014
XS GIS Cut Line= 3
2419408.73262411258118.0689896052419343.15204661257776.111668274
2419285.42775261257361.824111015
#Sta/Elev= 30
       0  488.29   16.27  488.38   29.29  489.14   81.35  487.88  139.93  483.15
  214.77  479.07   240.8   476.1  270.09  470.81  299.38  468.99  309.14  465.78
  315.65  463.02  325.41   461.6  336.21  461.18  348.19  460.73  357.81  461.45
  364.53  463.59  374.33  468.21   377.6  468.86  446.23  468.35   469.1  468.54
  482.17  469.24  488.71  471.13  501.78  476.11  518.12  481.03  563.87  492.45
  635.76  503.28  658.64  505.74  701.12  511.37     724  513.14  766.48  514.78
#Mann= 3 , 0 , 0
       0     .12       0  336.21    .045       0  357.81     .12       0
Bank Sta=336.21,357.81
XS Rating Curve= 0 ,0
Exp/Cntr=0.3,0.1

Type RM Length L Ch R = 1 ,12564.59,497.78,500,496.86
Node Name=1015
XS GIS Cut Line= 4
2419912.46061927258139.3202594372419803.52153268 257689.15974243
2419746.47210611257453.4197283542419676.92073603257394.810265526
#Sta/Elev= 30
       0  493.71   45.66  492.19  146.77  485.28  215.27  472.67  231.58  470.58
  251.15  469.16  260.93  467.05  300.07  467.86  319.64  466.82  362.04  467.86
  397.92  466.52  430.54   466.9  440.32  465.84  450.11  460.65  453.37  459.22
  463.15  458.38  469.71  459.18  472.87  461.39  479.54  465.21   486.1  467.67
  558.21  468.92  577.87  471.98  594.26  475.76  623.76  479.89  659.81  484.54
   705.7   487.2  734.93  491.99  747.93  492.69  767.42  496.41  796.65  500.36
#Mann= 3 , 0 , 0
       0     .12       0  450.11    .045       0  472.87     .12       0
Bank Sta=450.11,472.87
XS Rating Curve= 0 ,0
Exp/Cntr=0.3,0.1

Type RM Length L Ch R = 1 ,12064.59,497.66,500,500.02
Node Name=1016
XS GIS Cut Line= 3
2420452.96249102258262.8659441022420279.20299603257580.364028275
2420153.46932361257093.623203859
#Sta/Elev= 30
       0   478.8   68.79  476.24  167.06  470.47  265.33  466.42  452.05     465
  474.98  465.26   484.8  466.23  497.91  465.29  674.79  465.63  681.34  464.49
  694.45  457.42  697.72  455.48  704.27  455.08   710.8  455.91  715.45  457.38
  736.92  464.72  743.45  465.61  867.49  467.03  936.05  469.06  975.22  471.36
   994.8   471.7 1011.13  473.58 1017.66  474.94 1047.04  477.55 1060.09  479.38
 1122.12  483.01 1144.97  484.91 1171.08  488.08 1184.14  488.72 1206.99  487.74
#Mann= 3 , 0 , 0
       0     .12       0  694.45    .045       0  715.45     .12       0
Bank Sta=694.45,715.45
XS Rating Curve= 0 ,0
Exp/Cntr=0.3,0.1

Type RM Length L Ch R = 1 ,11564.59,513.4,511.38,508.6
Node Name=1017
XS GIS Cut Line= 3
2420869.76382278257959.4023121892420763.05406244257470.421662852
2420656.34397402256981.439701185
#Sta/Elev= 30
       0  476.87   49.07  475.07  121.03  469.17  202.81  464.99  271.51  464.15
  287.86  464.74  323.85  464.03   340.2  462.84  353.29  463.74  444.88  462.29
  464.51  462.49  474.32  461.47  484.13  454.86  489.64  453.41  500.49  452.54
  507.03  453.11  509.64  453.94  523.39   461.8  526.66   462.4  569.18  462.83
  582.27  462.38  667.32  463.64   749.1  465.21  817.79  467.64  843.96   469.5
  863.59  473.83  883.22  474.11  899.57  475.26  925.74  479.14 1000.98  486.95
#Mann= 3 , 0 , 0
       0     .12       0  489.64    .045       0  509.64     .12       0
Bank Sta=489.64,509.64
XS Rating Curve= 0 ,0
Exp/Cntr=0.3,0.1

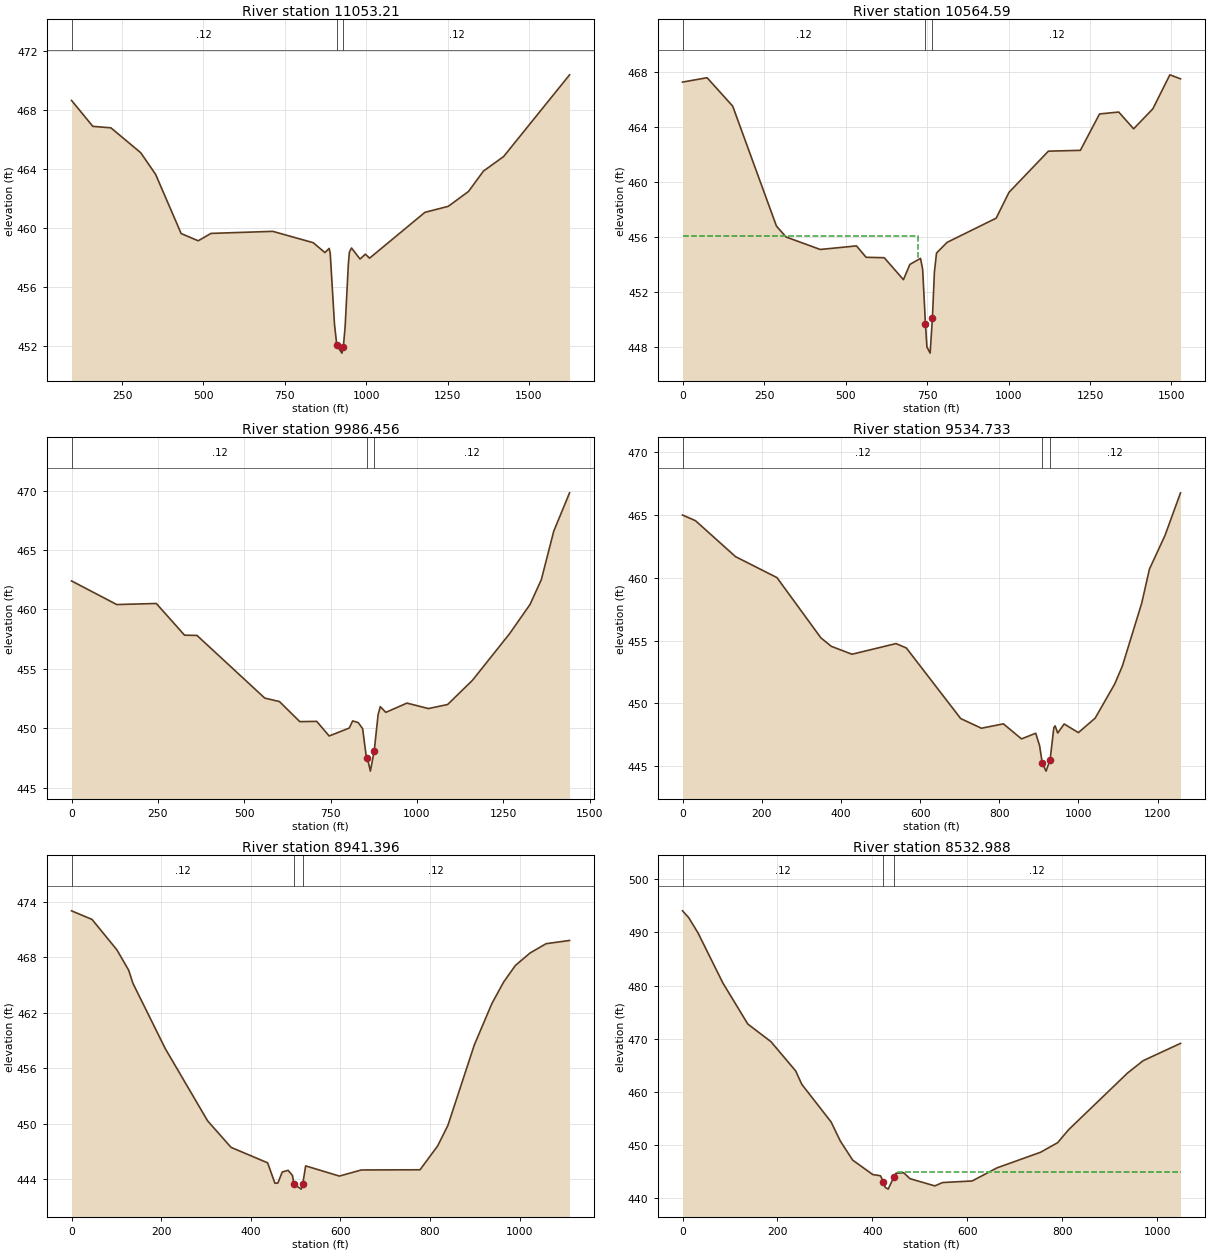
Type RM Length L Ch R = 1 ,11053.21,479.34,488.62,488.55
Node Name=1018
XS GIS Cut Line= 4
2421573.91560203258109.8095611422421402.71223195257831.314313769
 2421258.5871921257352.0744585992421056.29390242256679.278474909
#Sta/Elev= 30
   94.81  468.65  160.19  466.89  215.76  466.79   307.3   465.1  353.07  463.63
  431.53  459.61  483.87  459.12  523.12  459.62  712.83  459.76  837.12  458.99
   873.1  458.32  886.18   458.6  889.45  458.27  902.54  453.45  909.86  452.01
  925.43  451.49  929.84  451.94  935.23  453.28  945.04   457.5   948.3  458.35
  954.84  458.63  980.98  457.88  997.32  458.21 1010.39  457.94 1180.31  461.05
  1252.2  461.46 1314.29  462.47 1360.04  463.85 1422.12  464.84 1624.72  470.39
#Mann= 3 , 0 , 0
   94.81     .12       0  909.86    .045       0  929.84     .12       0
Bank Sta=909.86,929.84
XS Rating Curve= 0 ,0
Exp/Cntr=0.3,0.1

Type RM Length L Ch R = 1 ,10564.59,556.14,578.13,586.56
Node Name=1019
XS GIS Cut Line= 4
2421649.08870769257877.0802983492421773.30958785 257627.91609852
2421678.11817719257159.6040430222421518.88030669256404.858177185
#Sta/Elev= 30
       0  467.26   75.34  467.58  153.95  465.51  288.23  456.77  317.69  455.98
  422.43  455.07  533.72  455.33  563.18   454.5  618.83  454.47  677.75  452.87
  697.38  453.98  730.12  454.42  736.66  453.62  745.23  449.64  749.76  447.97
  759.57  447.52  766.65   450.1  772.65  453.41  779.18  454.81  811.87  455.59
  962.22  457.35 1001.44  459.23 1122.37  462.23 1220.43  462.29 1279.26  464.94
 1338.09  465.08 1383.85  463.86 1442.68  465.31 1494.98  467.79 1527.66   467.5
#Mann= 3 , 0 , 0
       0     .12       0  745.23    .045       0  766.65     .12       0
#XS Ineff= 2 , 0
           720.9  456.08
Permanent Ineff=
       F       F
Bank Sta=745.23,766.65
XS Rating Curve= 0 ,0
Exp/Cntr=0.3,0.1

Type RM Length L Ch R = 1 ,9986.456,442.02,451.72,429.47
Node Name=1020
XS GIS Cut Line= 5
2421785.38633536257954.3189890242422156.43250927257284.857729524
 2422174.7763046257216.3513048592422204.18569461257108.467662349
2422521.49739595256730.360807016
#Sta/Elev= 30
       0   462.4  130.84  460.41  245.32   460.5   327.1  457.83  363.08  457.81
  559.34  452.53  601.86  452.24  660.74  450.55   709.8  450.57  745.79  449.34
  804.09  450.01  813.77  450.61  829.88  450.47  842.72  449.95  852.31   447.8
  856.58  447.46  865.08  446.38  876.35  448.11  887.45  451.14  893.84  451.81
  909.81  451.33  971.03  452.11 1033.14  451.65 1088.72  451.99 1160.64  454.03
 1268.51  457.97 1327.35  460.42 1360.04  462.51    1396  466.59 1441.77  469.82
#Mann= 3 , 0 , 0
       0     .12       0  856.58    .045       0  876.35     .12       0
Bank Sta=856.58,876.35
XS Rating Curve= 0 ,0
Exp/Cntr=0.3,0.1

Type RM Length L Ch R = 1 ,9534.733,552.62,593.34,558.84
Node Name=1021
XS GIS Cut Line= 4
2421806.65368128 258117.947598772422406.95497411257603.037867442
2422480.00502487257403.7177280192422676.44524878257241.645545602
#Sta/Elev= 30
       0  465.01   32.68  464.56  133.99  461.69  238.57  460.02  349.69  455.21
  375.83  454.54  428.12  453.91  539.24  454.76  565.38  454.41  702.64  448.78
  754.93  448.01  810.48  448.36   856.2  447.16  892.12  447.61  901.92  446.62
  908.59  445.24  918.25  444.59  928.51  445.51  937.85  448.05  941.11   448.2
  947.65  447.63  963.98  448.35   999.9  447.66 1042.35  448.82 1091.32  451.52
 1110.91  452.96 1159.89  457.99 1179.48  460.71 1218.66  463.38 1257.84  466.78
#Mann= 3 , 0 , 0
       0     .12       0  908.59    .045       0  928.51     .12       0
Bank Sta=908.59,928.51
XS Rating Curve= 0 ,0
Exp/Cntr=0.3,0.1

Type RM Length L Ch R = 1 ,8941.396,421.76,408.41,386.37
Node Name=1022
XS GIS Cut Line= 4
2422932.67111428258335.625969186 2422786.1868272257958.021737516
2422784.13794677257853.580673441 2422756.3873461257252.068096936
#Sta/Elev= 30
       0  473.01   45.73  472.08  101.26  468.79  127.39  466.61  137.18  465.16
  209.04  458.14  303.77  450.32  356.03  447.46  437.67  445.79  453.99  443.58
  460.52  443.61  470.31   444.8  483.37  444.98  493.16  444.42  496.43  443.48
  512.76  442.95  516.03   443.5  522.57  445.46  597.84  444.36  646.93  445.02
  777.83  445.04   817.1  447.61  840.01  449.83  898.92  458.51  938.19  462.99
  964.37  465.31  990.55   467.1 1023.28  468.45 1059.27  469.46 1111.64  469.81
#Mann= 3 , 0 , 0
       0     .12       0  496.43    .045       0  516.03     .12       0
Bank Sta=496.43,516.03
XS Rating Curve= 0 ,0
Exp/Cntr=0.3,0.1

Type RM Length L Ch R = 1 ,8532.988,508.25,485.63,461.29
Node Name=1023
XS GIS Cut Line= 4
2423423.94736269257927.9292780162423284.85873011257906.056618348
2423130.43449828257669.5131281912422773.74295445257155.839286774
#Sta/Elev= 30
       0  494.08    13.1  492.79   32.74   489.9   85.13  480.46  137.52  472.74
  186.26  469.42  238.21  463.92   251.2  461.38  312.89  454.29  332.37  450.68
  358.35   447.1  400.56  444.38  416.79  444.15  423.19  442.96  426.56  441.99
  433.11  441.63  445.24  443.95  449.48  444.63  465.85  444.71  478.95   443.6
  531.34  442.24  547.71  442.87  609.92  443.17   662.3  445.64  753.98  448.58
     790  450.39  812.92  452.82  937.34  463.53  970.08  465.84 1048.66   469.1
#Mann= 3 , 0 , 0
       0     .12       0  423.19    .045       0  445.24     .12       0
#XS Ineff= 2 , 0
                           453.5          444.88
Permanent Ineff=
       F       F
Bank Sta=423.19,445.24
XS Rating Curve= 0 ,0
Exp/Cntr=0.3,0.1

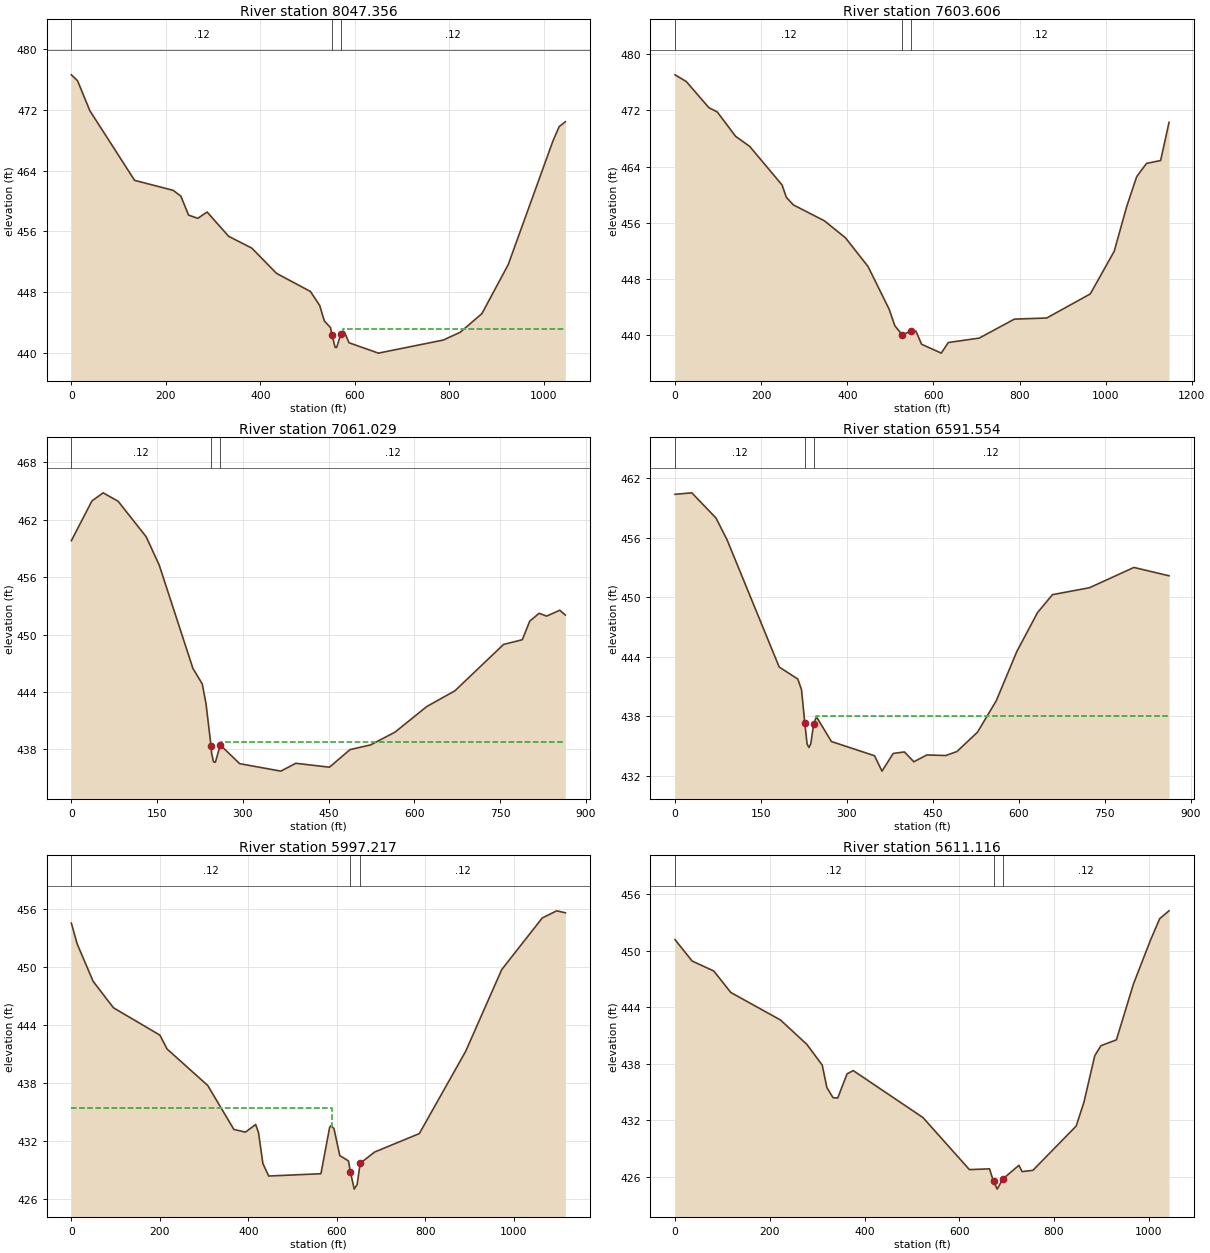
Type RM Length L Ch R = 1 ,8047.356,444.79,443.75,442.72
Node Name=1024
XS GIS Cut Line= 3
2423800.37082244257322.2464342712423310.65001711257222.840465099
2422776.99655686257105.587746859
#Sta/Elev= 30
       0  476.59   13.06  475.82   39.19  471.87  133.91  462.71  215.56   461.4
  231.89  460.64  248.22  458.14  267.82  457.72  287.41  458.55  333.14  455.35
  382.13   453.8  434.39  450.48  506.25   448.1  525.88  446.26   535.7  444.23
  548.78  443.34  552.06  442.33   558.6  440.74  561.87  440.75  570.76  442.51
  578.23  442.78  588.04  441.35  650.21  439.99  787.62  441.71  823.61  442.74
  869.41  445.19  925.03  451.62 1019.91  467.91    1033  469.78 1046.09  470.42
#Mann= 3 , 0 , 0
       0     .12       0  552.06    .045       0  570.76     .12       0
#XS Ineff= 2 , 0
                          575.31          443.14
Permanent Ineff=
       F       F
Bank Sta=552.06,570.76
XS Rating Curve= 0 ,0
Exp/Cntr=0.3,0.1

Type RM Length L Ch R = 1 ,7603.606,539.46,542.58,537.54
Node Name=1025
XS GIS Cut Line= 3
2423818.69460469256867.4924225212423278.32626286256766.694723859
 2422690.5196957256658.774664104
#Sta/Elev= 30
       0  477.06   26.18   476.1   78.53  472.39   98.16  471.77  140.69   468.3
  173.41  466.87  248.67  461.37  258.48  459.62  274.84  458.54  346.83  456.28
  395.91  453.85  448.26  449.77  497.34  443.68  510.43  441.34  527.59  440.05
  547.53  440.56  559.49  440.56  572.55  438.71  618.27  437.44   634.6  438.95
  706.45  439.58  788.09  442.28   863.2  442.44  964.44  445.87 1019.96  451.94
 1049.35  458.38 1072.21  462.57 1095.07  464.45 1127.73  464.86 1147.32  470.29
#Mann= 3 , 0 , 0
       0     .12       0  527.59    .045       0  547.53     .12       0
Bank Sta=527.59,547.53
XS Rating Curve= 0 ,0
Exp/Cntr=0.3,0.1

Type RM Length L Ch R = 1 ,7061.029,465.69,469.48,468.1
Node Name=1026
XS GIS Cut Line= 3
2423840.25361669256390.0753983562423342.55612127256337.230687767
2422980.80422011256301.196967185
#Sta/Elev= 30
       0  459.81   35.98  463.96   55.61  464.81   81.78  463.93  130.85  460.22
  153.75  457.25  212.63  446.46  228.98  444.84  235.53  442.76  244.24   438.4
  245.34  437.58  248.61  436.71  251.88  436.66  260.54  438.46  294.41  436.51
  366.38  435.73  392.55  436.55  451.43  436.14  487.41  437.98  523.42  438.47
     566   439.8  621.68  442.48   670.8  444.12  755.96  448.97  788.71  449.46
  801.81  451.41  818.19  452.22  831.29  451.93  854.21  452.54  864.04  452.04
#Mann= 3 , 0 , 0
       0     .12       0  244.24    .045       0  260.54     .12       0
#XS Ineff= 2 , 0
                          262.56          438.73
Permanent Ineff=
       F       F
Bank Sta=244.24,260.54
XS Rating Curve= 0 ,0
Exp/Cntr=0.3,0.1

Type RM Length L Ch R = 1 ,6591.554,576.29,594.34,593.46
Node Name=1027
XS GIS Cut Line= 4
2423845.76115161  255948.9158476 2423615.0529516255911.787641019
2423176.15323886255841.1545801912422995.61390178255876.303131938
#Sta/Elev= 30
       0  460.36   29.21  460.51    71.4  457.98   90.87  455.77  181.75  442.98
   214.2  441.77  220.69   440.7  226.55   437.3  230.43  435.23  233.68  434.88
  236.95  435.27  241.93  437.25  246.75  437.97   272.9  435.48  348.08  434.05
  361.16   432.5  380.77  434.28  400.38  434.43  416.73  433.44  439.61  434.13
  472.29  434.07  491.91  434.47  527.86  436.42  560.55  439.58  596.51  444.54
  632.46  448.44  658.61  450.26   723.4  450.96  800.84     453  862.15  452.16
#Mann= 3 , 0 , 0
       0     .12       0  226.55    .045       0  241.93     .12       0
#XS Ineff= 2 , 0
                          246.12          438.09
Permanent Ineff=
       F       F
Bank Sta=226.55,241.93
XS Rating Curve= 0 ,0
Exp/Cntr=0.3,0.1

Type RM Length L Ch R = 1 ,5997.217,381.36,386.1,384.54
Node Name=1028
XS GIS Cut Line= 3
2424279.03751603255727.6006734372423739.60946102255443.134706929
2423291.65464827255206.906832933
#Sta/Elev= 30
       0  454.51   13.11  452.37   49.18  448.51   95.08  445.78     200  442.96
  216.39  441.52   308.2  437.76  367.21  433.23  393.44  432.95   416.4  433.74
  422.95   432.9  432.79  429.71   445.9  428.42  563.94  428.66  583.61  433.44
  586.89  433.62  593.45  433.31  606.56  430.53  626.18  429.98  630.55  428.84
  639.24  427.07  645.78  427.55  652.55  429.73  684.99  430.89  786.27   432.8
  890.82  441.27  972.51  449.72 1063.99  455.04 1096.66  455.78 1116.26  455.58
#Mann= 3 , 0 , 0
       0     .12       0  630.55    .045       0  652.55     .12       0
#XS Ineff= 2 , 0
           589.6  435.46
Permanent Ineff=
       F       F
Bank Sta=630.55,652.55
XS Rating Curve= 0 ,0
Exp/Cntr=0.3,0.1

Type RM Length L Ch R = 1 ,5611.116,396.16,468.95,409.89
Node Name=1029
XS GIS Cut Line= 3
2424537.91199827255545.7138981072424071.83287795255267.153431609
2423642.77140011255010.716936603
#Sta/Elev= 30
       0  451.16   35.98   448.9   81.77  447.84  117.75  445.56  222.42  442.65
  278.03  440.07  310.74  437.86  320.55  435.47  333.64   434.4  343.45  434.38
  363.08  436.93  376.16  437.28  523.35   432.3  621.39  426.78  663.86  426.86
  672.27  425.52  680.19  424.71  691.65  425.77  725.93  427.24  732.47  426.57
  755.34   426.7  846.81   431.4  863.15  433.92  886.02  438.86  899.08  439.92
  931.75  440.54  967.69  446.46 1003.63  451.11 1023.23   453.4 1042.83  454.22
#Mann= 3 , 0 , 0
       0     .12       0  672.27    .045       0  691.65     .12       0
Bank Sta=672.27,691.65
XS Rating Curve= 0 ,0
Exp/Cntr=0.3,0.1

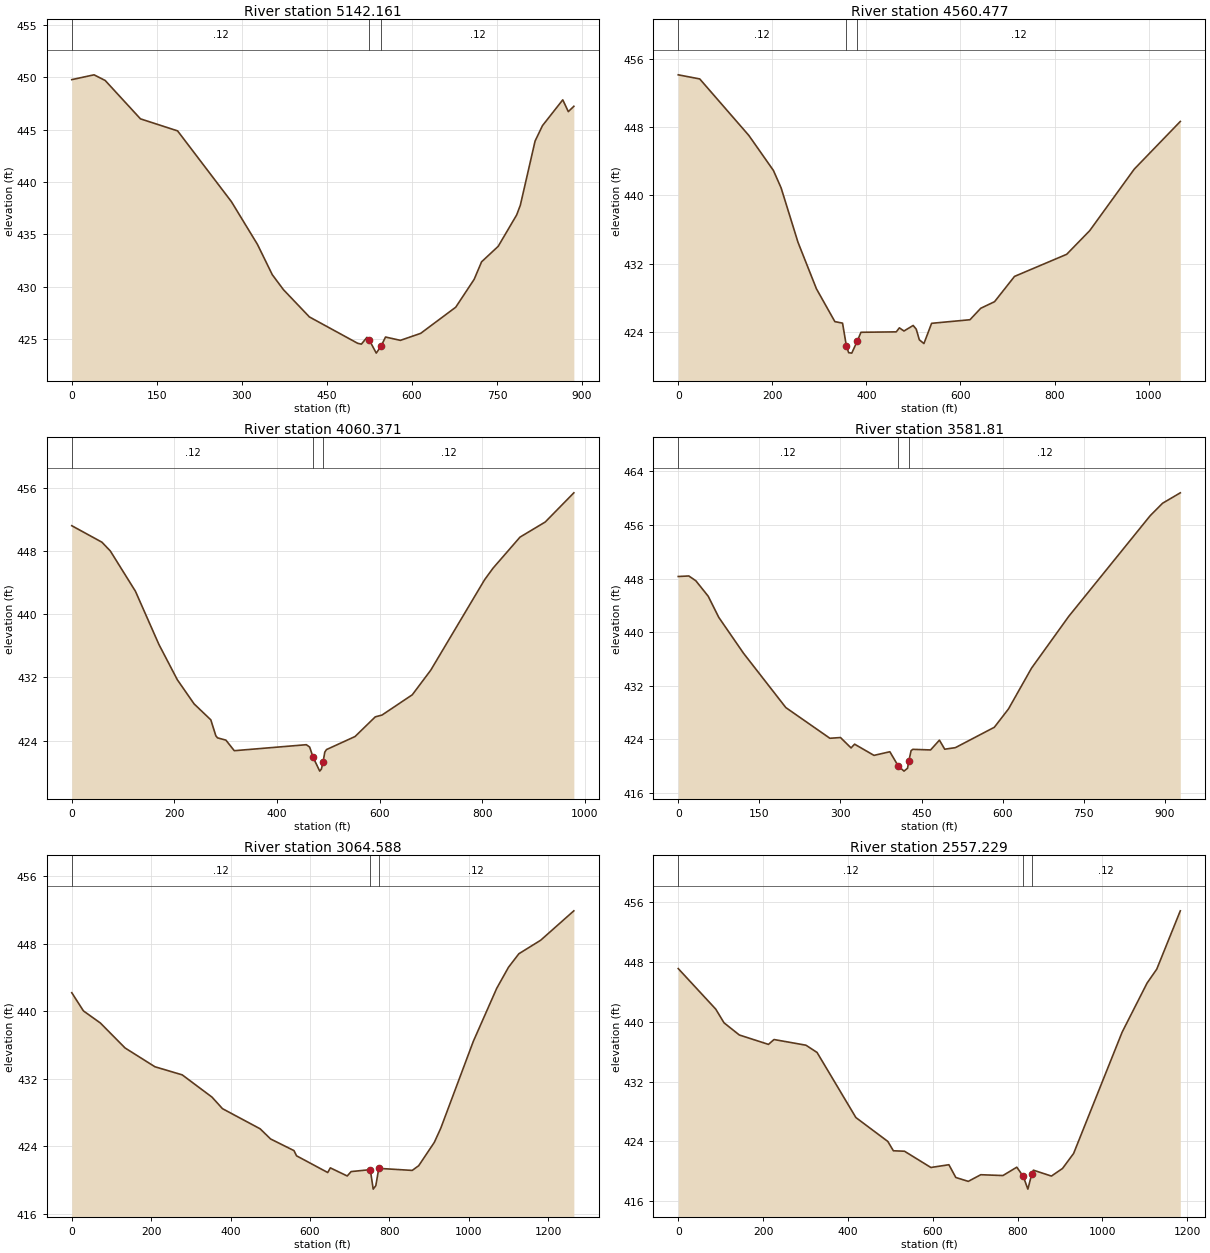
Type RM Length L Ch R = 1 ,5142.161,374.57,581.68,560.57
Node Name=1030
XS GIS Cut Line= 3
2424589.24227619255277.5789356832424153.16079928254905.804416776
2423915.37092052254703.080084682
#Sta/Elev= 30
       0  449.78   39.29  450.24   58.94   449.7  121.16  446.03  186.65  444.88
  281.61  438.11  327.46  434.03  353.65  431.13   373.3   429.7  419.14  427.09
  504.28  424.57  510.83  424.49  520.65  425.14  524.54   424.9  537.03  423.63
  545.31  424.28   553.4  425.17  579.56  424.85  615.36  425.52  677.21  428.02
  709.76  430.69  722.78  432.36  752.07  433.84  784.62  436.84  791.13  437.77
  817.17  443.91  830.19  445.38  865.99  447.85  875.76  446.72  885.52  447.23
#Mann= 3 , 0 , 0
       0     .12       0  524.54    .045       0  545.31     .12       0
Bank Sta=524.54,545.31
XS Rating Curve= 0 ,0
Exp/Cntr=0.3,0.1

Type RM Length L Ch R = 1 ,4560.477,460.29,500.11,503.36
Node Name=1031
XS GIS Cut Line= 3
2424638.28646944255053.4763655222424357.46846153254632.515593275
2424045.93824469254165.514886856
#Sta/Elev= 30
       0   454.1   45.71  453.62  150.18     447  202.41   442.9  218.74  440.86
  254.65  434.49  293.82  429.05     333  425.21  349.32  425.03  357.67   422.3
  362.38  421.57  368.91  421.52  380.32  422.89   388.5  423.96  463.59  424.01
  470.12  424.48  479.91  424.11   499.5  424.76  506.03  424.32  512.56  423.08
  522.35  422.64  538.67  425.01  620.26  425.43  643.11  426.77  672.48  427.54
  714.91   430.5  825.88  433.09  874.84  435.86  969.49  443.06 1067.41  448.64
#Mann= 3 , 0 , 0
       0     .12       0  357.67    .045       0  380.32     .12       0
Bank Sta=357.67,380.32
XS Rating Curve= 0 ,0
Exp/Cntr=0.3,0.1

Type RM Length L Ch R = 1 ,4060.371,410.93,478.56,424.15
Node Name=1032
XS GIS Cut Line= 3
 2424900.8633721254992.5798337762424760.42566086254533.592890859
2424614.56079511254056.871075273
#Sta/Elev= 30
       0  451.24   58.77  449.15    75.1  448.04  124.08  442.93  169.79  436.19
  205.71  431.71  238.36  428.65  271.02  426.62  280.81   424.6  284.08  424.34
   300.4  424.05  316.73  422.71  457.13  423.47  463.66  423.17   470.2   421.9
  483.27  420.12  486.55  420.39  489.83  421.29  493.11  422.52  496.39  422.85
  552.15  424.51  591.51     427  604.63  427.23  663.66   429.8  699.74  432.93
   804.7   444.4   821.1  445.86  873.57  449.79  922.77  451.71  978.53  455.41
#Mann= 3 , 0 , 0
       0     .12       0   470.2    .045       0  489.83     .12       0
Bank Sta=470.2,489.83
XS Rating Curve= 0 ,0
Exp/Cntr=0.3,0.1

Type RM Length L Ch R = 1 ,3581.81 ,494.63,517.22,494.73
Node Name=1033
XS GIS Cut Line= 3
2425140.36617394254917.7026869362425128.63981944254513.384597942
2425113.44299944253989.391879514
#Sta/Elev= 30
       0   448.3   19.57  448.38   32.62  447.66   55.45  445.36   75.03   442.2
  120.69  436.86  198.98  428.75  280.53  424.17   300.1  424.28  319.68  422.73
   326.2  423.29  362.08  421.62  391.44  422.16  406.85  420.05  417.59  419.27
  424.15   419.7  426.65  420.82   430.7  422.32  433.98  422.52  466.74  422.43
  483.12  423.89  492.95  422.54  512.61  422.77  584.69  425.81   610.9  428.55
  653.49  434.63  722.29  442.35     873  457.37  895.94  459.23   928.7  460.78
#Mann= 3 , 0 , 0
       0     .12       0  406.85    .045       0  426.65     .12       0
Bank Sta=406.85,426.65
XS Rating Curve= 0 ,0
Exp/Cntr=0.3,0.1

Type RM Length L Ch R = 1 ,3064.588,473.22,507.36,488.88
Node Name=1034
XS GIS Cut Line= 4
2425682.30373836255185.2730179432425550.83713777254434.412643015
2425481.69521569254067.5531405212425366.06913461254011.244198024
#Sta/Elev= 30
       0  442.21   29.44  440.05   71.98  438.62  134.14  435.66  209.38  433.43
  278.09  432.47  353.33  429.82  379.51  428.46  474.38  426.07  500.55  424.87
  559.44  423.49  565.99  422.87  644.51  420.89  651.05  421.44  693.58  420.48
  703.39     421  751.66  421.23  759.01  418.92  765.56  419.33   773.1  421.38
  857.25  421.14  873.62   421.7  912.92  424.47  929.29  426.16 1011.16  436.45
 1070.11  442.74 1099.58  445.22 1125.78  446.83 1180.62  448.43 1264.21  451.92
#Mann= 3 , 0 , 0
       0     .12       0  751.66    .045       0   773.1     .12       0
Bank Sta=751.66,773.1
XS Rating Curve= 0 ,0
Exp/Cntr=0.3,0.1

Type RM Length L Ch R = 1 ,2557.229,497.78,496.35,443.81
Node Name=1035
XS GIS Cut Line= 3
2426051.83318302255172.2684507672425996.50356928254579.294571102
2425941.15591094253993.883012265
#Sta/Elev= 30
       0  447.14   88.35  441.71  107.98  439.87  143.98  438.24   212.7  436.98
  225.79  437.63  301.05  436.87  327.23   435.9  418.85  427.17  494.11  423.97
   507.2  422.72  533.38  422.66  595.55  420.48  638.02  420.85  654.35  419.14
  683.75  418.62  713.15  419.51  765.42   419.4  798.09  420.52  813.33  419.29
  824.23  417.58  833.65  419.65  837.29  420.12  879.76  419.33   905.9  420.35
  932.03  422.36 1046.37  438.61 1105.17  445.19 1128.04  447.06 1183.58  454.88
#Mann= 3 , 0 , 0
       0     .12       0  813.33    .045       0  833.65     .12       0
Bank Sta=813.33,833.65
XS Rating Curve= 0 ,0
Exp/Cntr=0.3,0.1

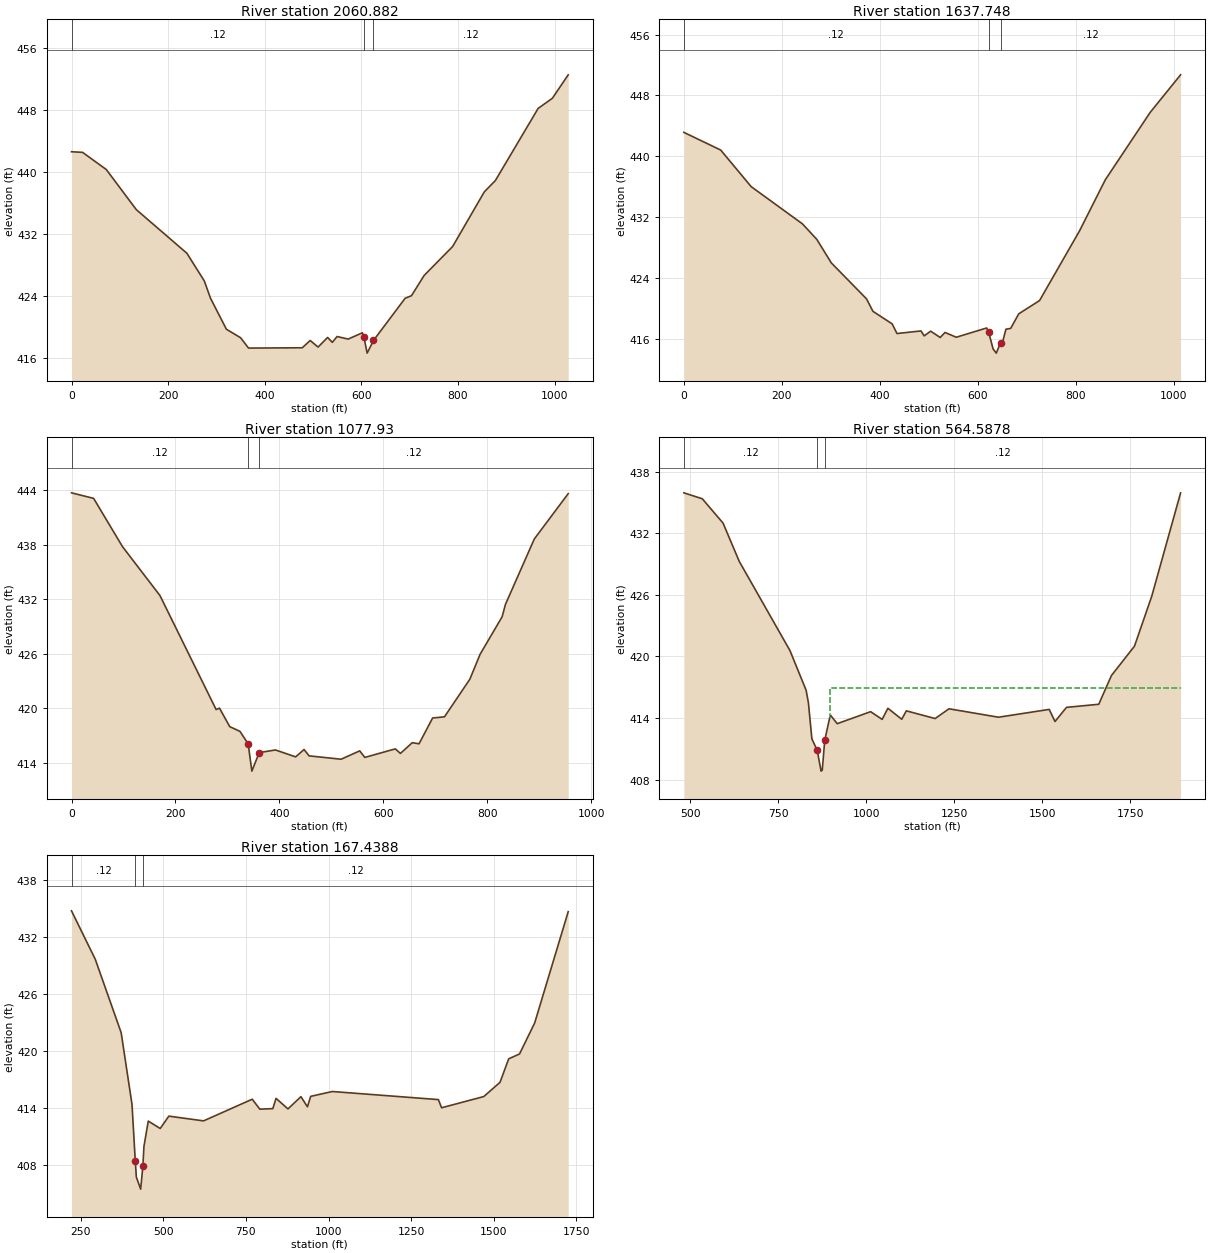
Type RM Length L Ch R = 1 ,2060.882,415.38,423.13,421.16
Node Name=1036
XS GIS Cut Line= 3
2426739.81343436254784.1632558552426447.96231203254377.353702024
2426140.37565686 253948.61046502
#Sta/Elev= 30
       0  442.61   22.91  442.53   71.99  440.32  134.17  435.15  238.88  429.53
  274.88  425.97  287.97  423.71  320.69  419.74  350.14  418.64   366.5  417.31
  477.76  417.35  494.13  418.29   510.5  417.44  530.17  418.68     540  418.05
  549.83   418.8  572.77  418.47  602.27  419.28  605.55  418.68   612.1  416.66
  625.21  418.29  690.76  423.73  703.87  424.06  730.09  426.67  789.09   430.4
  854.63  437.44  877.58   438.9  966.07  448.19  995.56   449.5 1028.34  452.52
#Mann= 3 , 0 , 0
       0     .12       0  605.55    .045       0  625.21     .12       0
Bank Sta=605.55,625.21
XS Rating Curve= 0 ,0
Exp/Cntr=0.3,0.1

Type RM Length L Ch R = 1 ,1637.748,546.81,559.82,542.28
Node Name=1037
XS GIS Cut Line= 3
2427031.65077719254634.508043349 2426713.4722797254081.512102097
2426524.65179119253756.067214936
#Sta/Elev= 30
       0  443.15   75.25  440.82  137.41  436.01  242.11  431.11  271.56  429.06
     301  425.98  372.98  421.24  386.07   419.6  425.33  417.95  435.15  416.68
  484.22  417.02  490.77  416.37  503.85  416.99  523.49  416.16   533.3  416.82
   556.2  416.19  618.37  417.41  622.48  416.82  631.45  414.65     638   414.1
  646.64  415.48  651.09  415.63  657.63  417.24  667.44  417.36   683.8  419.27
  726.34  421.02  808.13  430.21  860.48   436.9  952.09  445.77 1014.25  450.72
#Mann= 3 , 0 , 0
       0     .12       0  622.48    .045       0  646.64     .12       0
Bank Sta=622.48,646.64
XS Rating Curve= 0 ,0
Exp/Cntr=0.3,0.1

Type RM Length L Ch R = 1 ,1077.93 ,482.9,513.34,532.45
Node Name=1038
XS GIS Cut Line= 4
2427328.28797919254275.5540368562427174.49891669253953.476925105
2427108.18343252253805.7429686042426673.13082494253763.354930013
#Sta/Elev= 30
       0  443.73   42.57  443.12   98.23   437.8  170.27  432.42  278.32  419.87
  284.87  420.02  304.52  417.99  324.17  417.47  340.04  416.09  347.09  413.09
  361.31  415.13  392.54  415.42   431.4  414.66  447.59  415.47  457.31  414.77
  518.85   414.4  554.73  415.32  564.51   414.6  623.23  415.54  633.02  415.04
  655.85  416.22   668.9   416.1     695  418.94  717.83  419.07  766.76  423.22
  786.33  425.95  828.74  430.08  835.26  431.46  890.72  438.65  955.96  443.64
#Mann= 3 , 0 , 0
       0     .12       0  340.04    .045       0  361.31     .12       0
Bank Sta=340.04,361.31
XS Rating Curve= 0 ,0
Exp/Cntr=0.3,0.1

Type RM Length L Ch R = 1 ,564.5878,417.4,397.15,361.98
Node Name=1039
XS GIS Cut Line= 4
2427523.91053013254295.0501716142427653.10097785253927.019300848
 2427685.6589836253834.3803785152426766.54382186 253743.92619635
#Sta/Elev= 30
  481.83  435.93  534.27  435.35  593.27  432.98  639.16  429.26  783.38  420.57
  829.27  416.71  835.82  415.49  845.65  411.98  860.83  410.85  871.88  408.83
  875.15  408.92  882.22  411.83  898.06   414.3   917.7  413.45 1012.64  414.62
 1045.39  413.87 1061.77  414.95 1101.07  413.88 1114.17   414.7 1196.04  413.95
 1235.34   414.9 1376.17  414.08 1520.27  414.84 1536.65  413.66  1569.4  415.04
  1661.1  415.34 1697.12  418.14 1762.62     421 1811.75  425.87 1893.62  435.92
#Mann= 3 , 0 , 0
  481.83     .12       0  860.83    .045       0  882.22     .12       0
#XS Ineff= 2 , 0
                          895.82          416.92
Permanent Ineff=
       F       F
Bank Sta=860.83,882.22
XS Rating Curve= 0 ,0
Exp/Cntr=0.3,0.1

Type RM Length L Ch R = 1 ,167.4388,165.44,167.44,147.75
Node Name=1040
XS GIS Cut Line= 4
2428063.08305201254168.5948209532428000.19116294254039.341910854
2427879.72814928253791.5668158532426798.32205276253719.735410334
#Sta/Elev= 30
  222.14  434.72  294.01  429.63  372.44   421.9  405.24  414.35  415.08  408.44
  418.36  406.71  431.48  405.44  438.04  407.85  441.38  409.94  454.44   412.6
  490.52  411.82  516.75  413.12  621.71  412.62  769.09   414.9  792.01  413.85
   831.3  413.91  841.12  414.99  877.14  413.88  916.43  415.17  936.08   414.1
   945.9   415.2 1011.39  415.71 1332.27  414.86 1342.09     414 1469.79  415.18
 1518.91  416.68  1545.1  419.15 1577.84  419.66 1623.68  422.92 1725.19  434.63
#Mann= 3 , 0 , 0
  222.14     .12       0  415.08    .045       0  438.04     .12       0
Bank Sta=415.08,438.04
XS Rating Curve= 0 ,0
Exp/Cntr=0.3,0.1

River Reach=UNT1ToLngMrshRn ,Reach1
Reach XY= 30
2432025.15850669255551.0403310212432132.89582403255506.948883772
 2432147.5280126255537.3553190232432158.59065452255535.297252268
2432168.57062145255522.2273965182432197.72640303255526.116824433
2432218.54525903255508.001047015 2432364.2027761255504.371461108
2432387.46913378255511.9941492682432407.66824035255494.325877517
2432437.98970203255445.1540598572432458.72063169255442.689825937
2432471.57854562255458.0024593472432481.56605844255455.223265439
2432500.91641344 255428.897530692432554.48290735255404.702697188
2432563.51077645255385.6052944362432593.62915452 255359.46755144
2432616.80922627255315.6402112692432649.96893686255295.674700022
2432652.74681844255222.7581791882432782.95521945255147.063776776
2432781.91355486 255092.029109942432821.67036511255078.834582523
2432862.98983628255034.7372297642432892.67744094255014.945602685
2432899.21286094254991.7950584292432949.44799669254918.765020773
2432988.85802285254897.7581730192433022.63977945254893.915004849