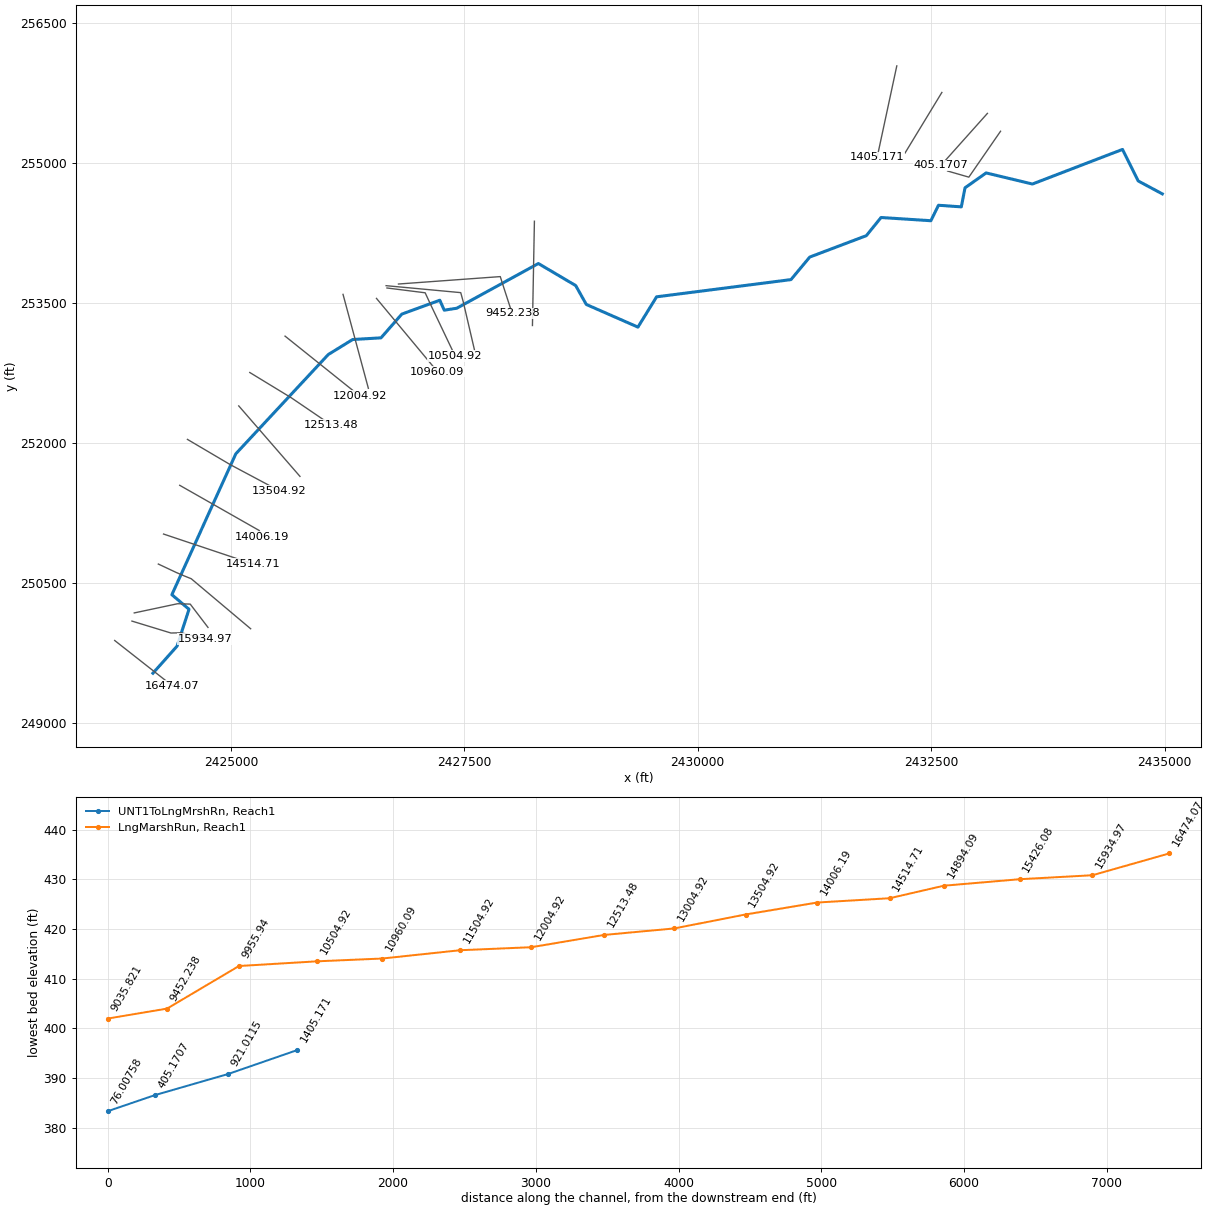
HEC-RAS study LongMarshRun.prj: Long Marsh Run

--- LongMarshRun.g01 (geometry) --- (continued)

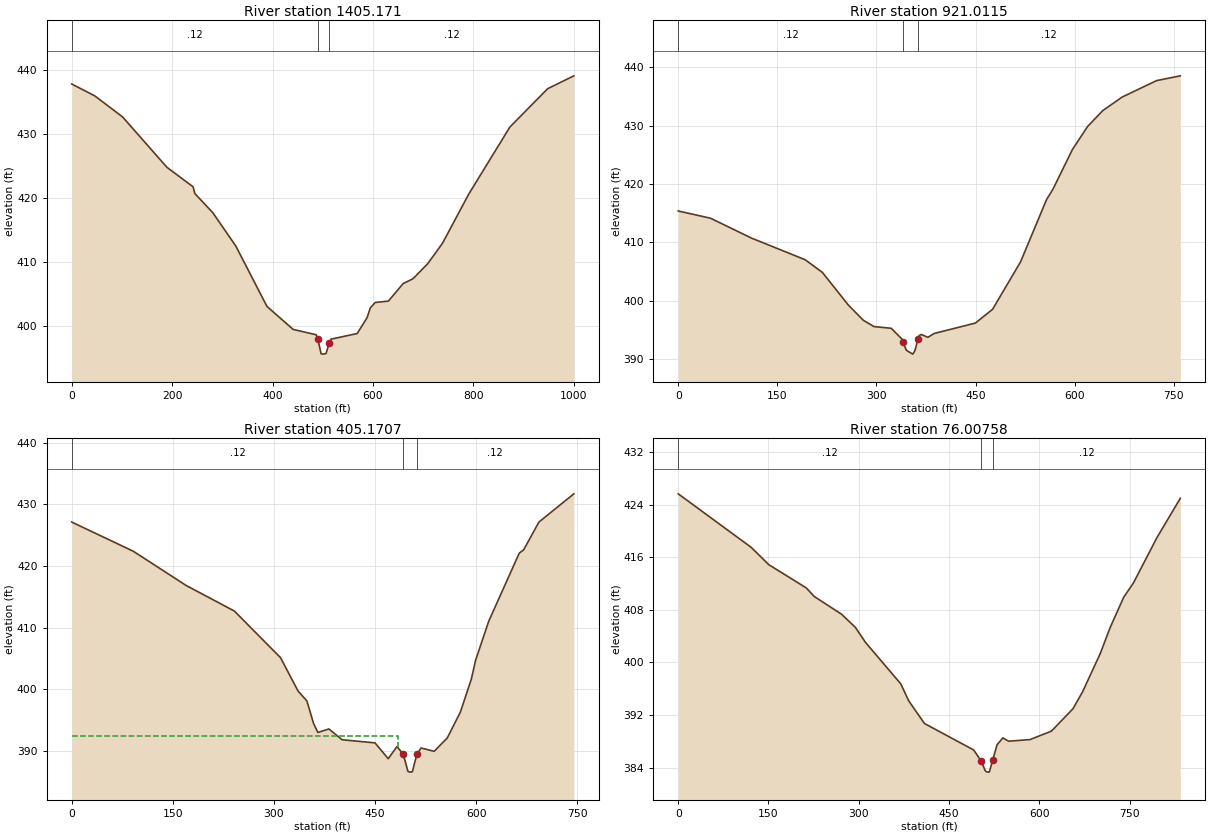
Type RM Length L Ch R = 1 ,1405.171,470.07,484.16,439.61
Node Name=1008
XS GIS Cut Line= 3
2432132.17305644 256039.563632192432027.12011695255550.650568023
2431921.99959227255061.422871932
#Sta/Elev= 30
       0  437.87   45.76  436.02  101.32  432.72  189.57  424.85  241.86  421.79
  245.13  420.75  281.09  417.74  326.84  412.54  388.94  403.09  441.24  399.49
     487  398.66  490.45  397.95   496.8   395.7  500.07  395.63  506.61  395.71
  513.15  397.39  516.42  397.97  568.75  398.85  588.38  401.32  594.92  402.86
  604.73  403.71  630.89  403.92  660.33  406.66  679.95  407.42  709.39  409.78
  738.82  412.98  791.15  420.67  872.91  431.13  948.14  437.13 1000.46  439.15
#Mann= 3 , 0 , 0
       0     .12       0  490.45    .045       0  513.15     .12       0
Bank Sta=490.45,513.15
XS Rating Curve= 0 ,0
Exp/Cntr=0.3,0.1

Type RM Length L Ch R = 1 ,921.0115,504.74,515.84,489.76
Node Name=1009
XS GIS Cut Line= 3
2432614.81513578255754.9618391842432426.98349044255446.113703609
2432219.95634544255105.702967107
#Sta/Elev= 30
       0  415.35   48.85  414.11  110.72  410.71  192.14  406.99  218.19  404.82
  257.27  399.25  280.07  396.62  296.35  395.53   322.4  395.24  338.68  393.38
  340.03  392.89   345.2  391.48  354.97  390.81  358.22  391.39  362.76  393.37
  364.75  394.01  368.01  394.18  377.81  393.69  387.61  394.36  449.66  396.13
  475.78  398.49  518.24  406.66  557.43   417.3  567.22   419.1  596.62  425.89
  619.48  429.82  642.34  432.54  671.73  434.87  723.98   437.7   759.9  438.52
#Mann= 3 , 0 , 0
       0     .12       0  340.03    .045       0  362.76     .12       0
Bank Sta=340.03,362.76
XS Rating Curve= 0 ,0
Exp/Cntr=0.3,0.1

Type RM Length L Ch R = 1 ,405.1707,314.99,329.16,327.97
Node Name=1010
XS GIS Cut Line= 3
2433102.69211277255530.6496237672432767.91686369255156.286199272
2432606.01200378254975.235708356
#Sta/Elev= 30
       0  427.12   91.31  422.39  169.58  416.84  241.33  412.68  309.81  405.11
   335.9  399.68  348.94  398.09  358.73  394.46  365.25  392.97  381.56  393.54
  401.12  391.79  450.04  391.28  469.61  388.71  482.65  390.69  491.95  389.42
  498.96  386.64  502.22  386.53  505.46   386.6  512.18  389.45  518.41  390.45
  537.84  389.91  557.27  392.08   576.7  396.27  592.89   401.6  599.37  404.72
   618.8  411.03  664.14  422.09  670.62  422.62  693.29  427.13   745.1  431.71
#Mann= 3 , 0 , 0
       0     .12       0  491.95    .045       0  512.18     .12       0
#XS Ineff= 2 , 0
          483.59  392.38
Permanent Ineff=
       F       F
Bank Sta=491.95,512.18
XS Rating Curve= 0 ,0
Exp/Cntr=0.3,0.1

Type RM Length L Ch R = 1 ,76.00758,64.67,76.01,63.34
Node Name=1011
XS GIS Cut Line= 4
2433243.39918044255339.5647041052432958.83118002254927.456276357
 2432903.8827991254847.8806481062432676.25792627254913.387734935
#Sta/Elev= 30
       0  425.63  121.11   417.5  150.57  414.85  212.76  411.32  225.86  410.03
  271.68   407.3   294.6   405.3  310.96  403.06  369.88  396.72  382.97  394.15
  409.16   390.7  490.99  386.67  503.23  385.02  510.48  383.47  513.71   383.3
  516.93  383.32  522.62  385.13  529.82  387.45  539.49  388.51  549.16     388
  584.62  388.25  620.23  389.54  655.92  392.93  672.14  395.55  701.35  401.34
  717.57  405.24  740.28   409.9  756.51  412.08  795.44  418.95  834.38  424.95
#Mann= 3 , 0 , 0
       0     .12       0  503.23    .045       0  522.62     .12       0
Bank Sta=503.23,522.62
XS Rating Curve= 0 ,0
Exp/Cntr=0.3,0.1

River Reach=LngMarshRun     ,Reach1
Reach XY= 30
2424165.03511935249534.8640431912424423.37252919249824.371994346
2424551.62785012250219.4240257742424368.03405719250375.804290444
2425052.82861936251884.7317187642426042.92539245252947.896259099
2426304.29166761253108.7673284412426607.81271411253126.715783358
2426830.90281911253380.838962764 2427237.5870451 253529.71038419
 2427284.9553887253422.9720806032427418.26450528253443.496973932
2428293.35953985253922.7227215172428693.09889786253686.611645192
2428806.81422161253484.1376406852429359.76587161253241.660763443
2429559.50530152253566.0531592672430998.82821028253750.428118601
2431199.86980294253991.8344599312431806.08315744254221.168318853
2431963.31775111254415.4802661842432496.91838995254381.157172099
2432578.93627052 254546.753953772432823.30750094254529.421311274
 2432862.8907551254733.5878976882433088.93229778254892.962907016
2433584.82303828254774.084207773 2434549.6511611255144.755054355
2434717.83684836254806.8643259412434975.69361611254668.721557602

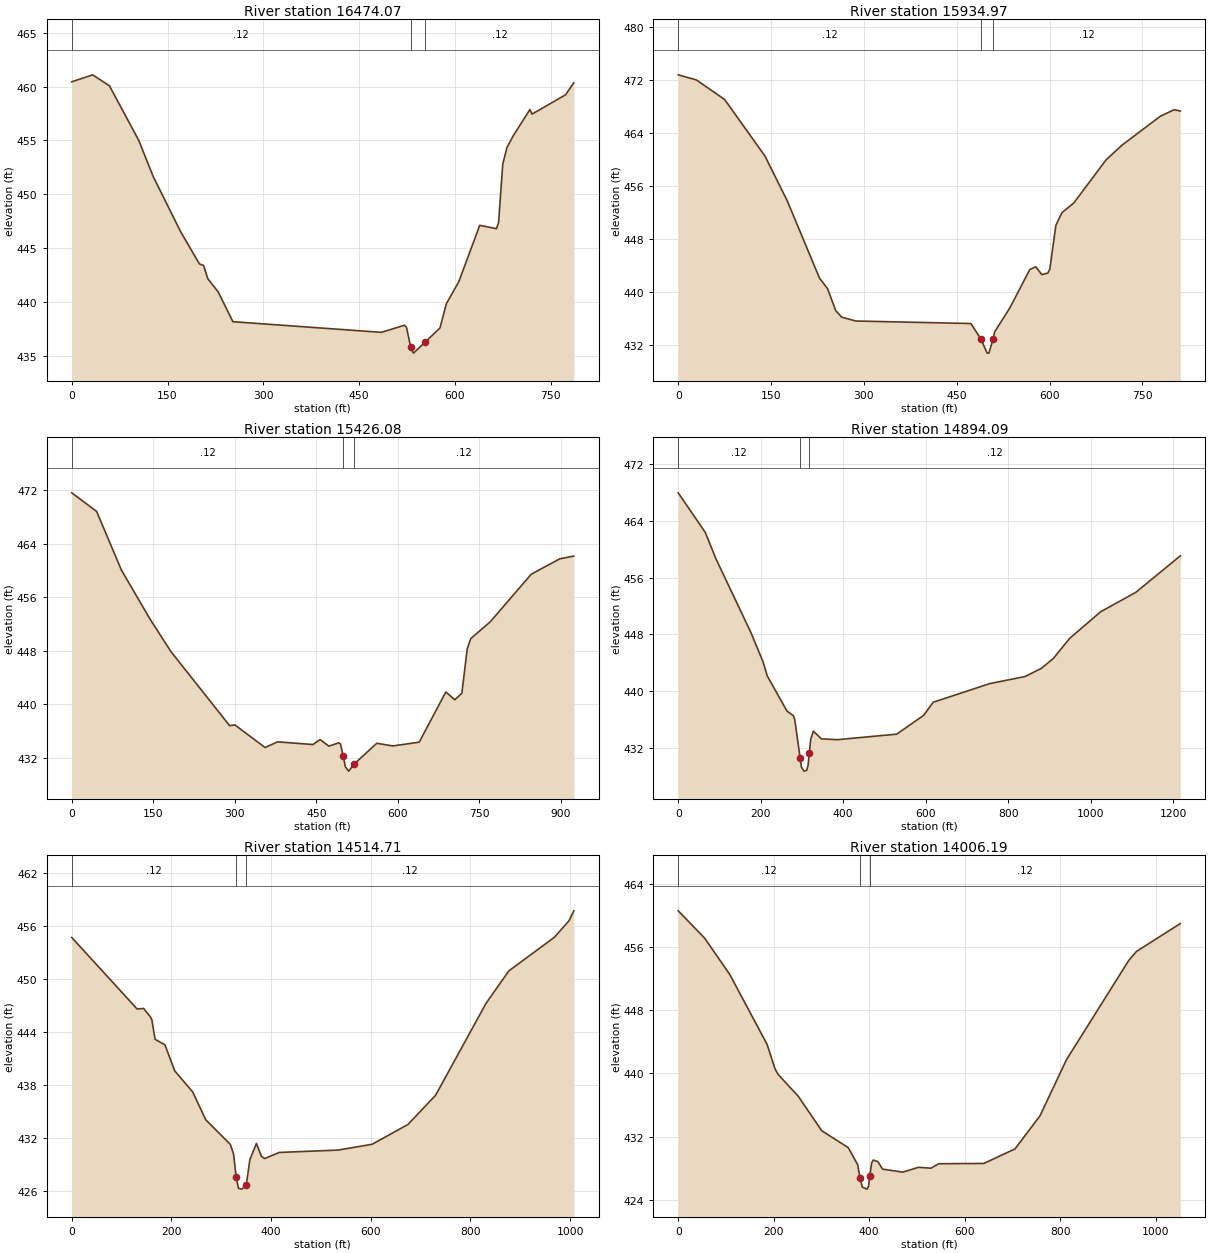
Type RM Length L Ch R = 1 ,16474.07,515.93,539.1,550.64
Node Name=974
XS GIS Cut Line= 3
2423755.49591219249885.2468726042424152.25725777249573.548020944
2424373.70924269249399.573631346
#Sta/Elev= 30
       0  460.45   32.76   461.1   58.97  460.08  104.84  455.02  127.78  451.62
  170.37  446.54  199.86  443.54  206.41  443.39  212.96  442.17  229.34  440.93
  252.28  438.17   484.9  437.18  520.93  437.84   524.2  437.64  530.75  435.78
  535.07  435.25  553.67  436.29   576.6  437.59  586.42  439.82  606.07  441.89
  638.81  447.12  665.01  446.81  668.29  447.37  674.84  452.79  681.38  454.34
  691.21  455.43  717.41  457.88  720.68  457.45  773.07  459.24  786.17  460.36
#Mann= 3 , 0 , 0
       0     .12       0  530.75    .045       0  553.67     .12       0
Bank Sta=530.75,553.67
XS Rating Curve= 0 ,0
Exp/Cntr=0.3,0.1

Type RM Length L Ch R = 1 ,15934.97,469.18,508.89,451.2
Node Name=975
XS GIS Cut Line= 5
2423940.36627735250092.9370740212424358.29162261249965.246384516
2424420.18651195249966.7335862672424466.58176036249968.935353518
2424723.91654752249901.702548355
#Sta/Elev= 30
       0  472.79   29.35  472.02   75.01  469.07  140.23  460.54   176.1  453.81
  228.28  442.16  241.33  440.56  254.37  437.28  264.16  436.27  286.98  435.69
  472.84  435.31  489.34  432.95  498.91  430.88  502.01  430.85  508.76  432.96
   511.3  434.04  536.07   437.7  568.06  443.44  577.79  443.87  587.52  442.68
  597.25  442.91   600.5  443.52  610.23  450.09  619.96  452.01  639.42   453.5
  691.32  459.97  717.27   462.2   778.9  466.54   801.6  467.54  811.33  467.33
#Mann= 3 , 0 , 0
       0     .12       0  489.34    .045       0  508.76     .12       0
Bank Sta=489.34,508.76
XS Rating Curve= 0 ,0
Exp/Cntr=0.3,0.1

Type RM Length L Ch R = 1 ,15426.08,434.41,531.98,392.39
Node Name=976
XS GIS Cut Line= 5
2423965.11786827250180.5018595162424428.03262486250278.655862689
2424464.40919253250278.3884747772424564.64455636250274.805804774
2424755.03033045250025.075989276
#Sta/Elev= 30
       0   471.6   45.69  468.83   91.38  460.07  143.59   452.8  182.76  447.87
  290.45  436.84  300.24  436.95  355.72  433.57  378.57  434.42  443.84  434.02
  456.89  434.76  473.21  433.78   491.4  434.28  494.43   434.1  499.42  432.36
  503.52  430.69  509.58  430.05  519.72  431.12  561.35  434.21  590.47  433.81
  639.32  434.37  688.39  441.87  704.75  440.71  717.83  441.66  727.64  448.28
  734.19  449.84  770.17  452.35   845.4  459.44  897.74  461.74  923.91  462.16
#Mann= 3 , 0 , 0
       0     .12       0  499.42    .045       0  519.72     .12       0
Bank Sta=499.42,519.72
XS Rating Curve= 0 ,0
Exp/Cntr=0.3,0.1

Type RM Length L Ch R = 1 ,14894.09,375.16,379.38,377.38
Node Name=977
XS GIS Cut Line= 5
2424222.98841552250703.9640671912424415.30594428250613.469169438
2424503.30511211250575.5574998562424575.20194994250546.802636102
2425211.67147753250011.039600015
#Sta/Elev= 30
       0  467.96    65.4   462.4   91.56  458.65  176.58  448.23  206.01   444.1
  215.74  442.18  263.65  437.21  279.62  436.54  282.81  435.93  295.59  430.62
  298.78  429.31  305.17  428.74  311.59  428.85  314.82  429.54  318.04  431.34
  321.27   433.2  327.72  434.38  347.08  433.29   385.8  433.17  529.91  433.95
  595.42  436.61  618.35  438.45  755.92  441.08  841.08  442.07  880.38  443.21
  909.86  444.62  949.16  447.44  1024.5   451.2 1109.66  453.93 1217.74  459.08
#Mann= 3 , 0 , 0
       0     .12       0  295.59    .045       0  318.04     .12       0
Bank Sta=295.59,318.04
XS Rating Curve= 0 ,0
Exp/Cntr=0.3,0.1

Type RM Length L Ch R = 1 ,14514.71,502.69,508.53,497.38
Node Name=978
XS GIS Cut Line= 3
2424278.92563961251025.2701831012424754.75638086 250865.88336277
2425234.41847928250705.213080436
#Sta/Elev= 30
       0   454.7  131.19  446.61  144.31  446.67  157.43  445.75  160.71   445.4
  167.27  443.17  186.95  442.56  206.63  439.61  242.71  437.22  268.95  434.07
  318.14  431.29   324.7  430.21  329.88  427.61  334.54  426.32   341.1  426.22
  350.19  426.68   357.5  429.57  370.62  431.39  380.46  429.94  387.02  429.68
  416.54  430.37  534.45  430.64  602.99   431.3  674.79  433.54  730.27  436.85
  831.44  447.25  877.13  450.92  968.51  454.72  997.88  456.59 1007.67  457.72
#Mann= 3 , 0 , 0
       0     .12       0  329.88    .045       0  350.19     .12       0
Bank Sta=329.88,350.19
XS Rating Curve= 0 ,0
Exp/Cntr=0.3,0.1

Type RM Length L Ch R = 1 ,14006.19,498.22,501.26,498.18
Node Name=979
XS GIS Cut Line= 4
2424451.96367936251547.2963700152424886.46838778251300.311299682
2425303.43277694 251063.297009932425332.49013352250997.389333352
#Sta/Elev= 30
       0  460.56   55.53  457.09   107.8  452.52   186.2  443.65  202.53  440.59
  209.06  439.87  251.53  437.09  300.53  432.74  356.06   430.6  375.66  428.45
  380.77  426.79  385.46  425.61  395.26  425.35  398.53  425.68  401.11  427.05
  405.06  428.66  408.33  429.03  418.13  428.83  427.93  427.88   470.4   427.5
  503.06  428.11  529.16     428  545.47  428.56  640.09   428.6  705.35  430.44
  757.55  434.62  813.02  441.72  943.53  454.29  959.84  455.43 1051.45  458.95
#Mann= 3 , 0 , 0
       0     .12       0  380.77    .045       0  401.11     .12       0
Bank Sta=380.77,401.11
XS Rating Curve= 0 ,0
Exp/Cntr=0.3,0.1

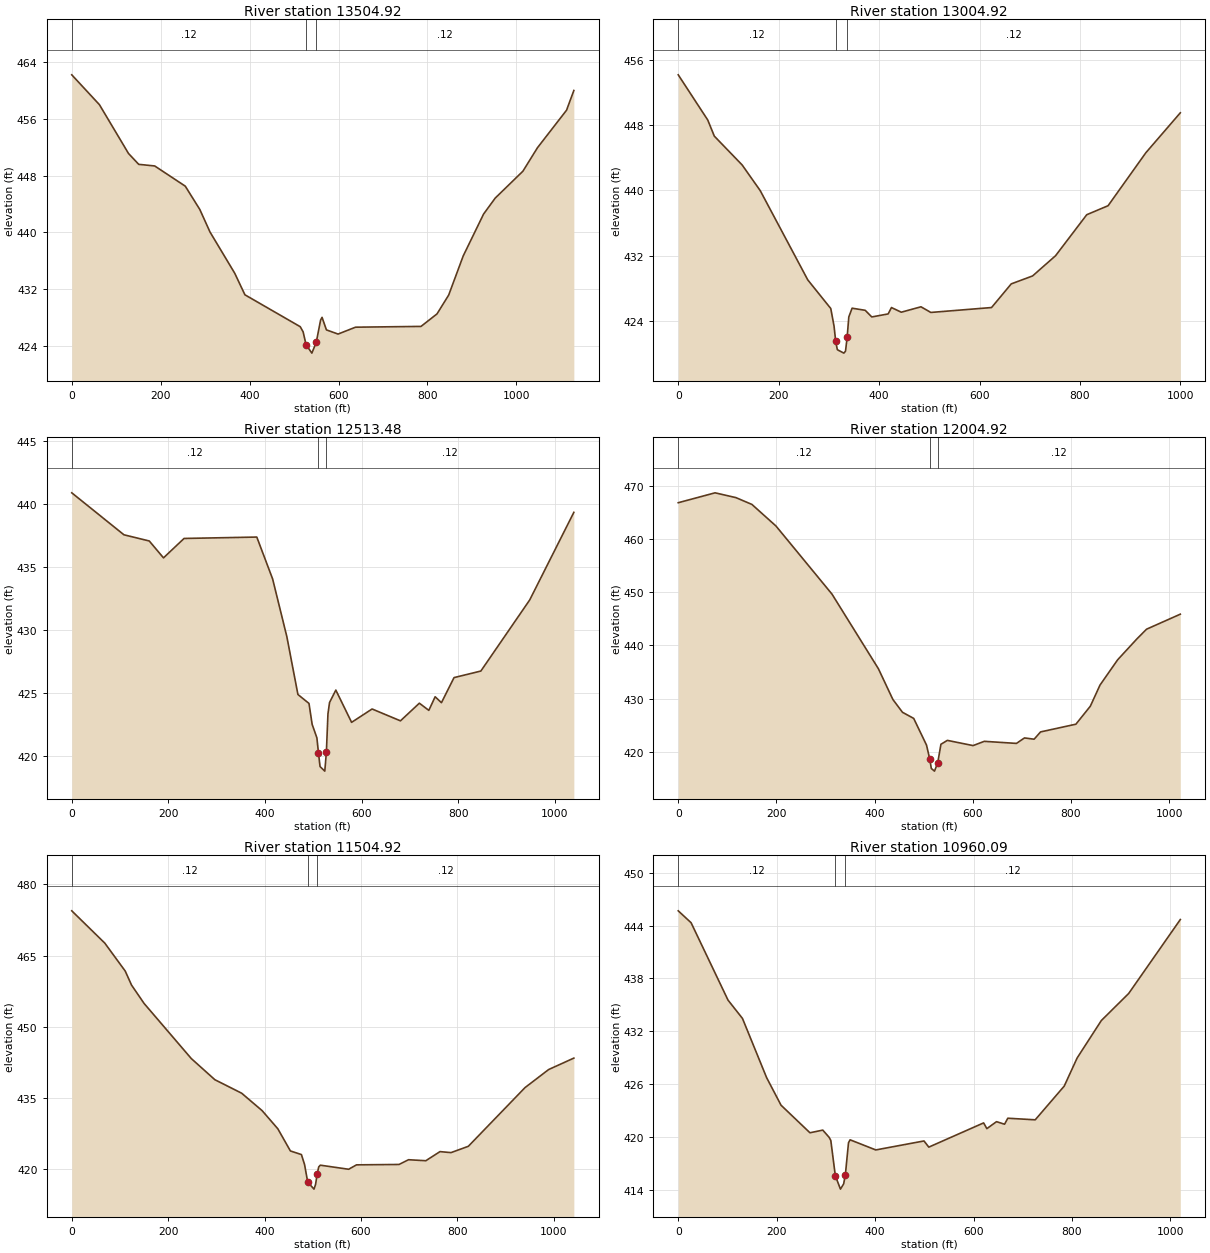
Type RM Length L Ch R = 1 ,13504.92,505.65,500,485.45
Node Name=980
XS GIS Cut Line= 3
2424534.74697836252039.0558851812424997.12794335251766.496719018
2425519.99008662251487.840452179
#Sta/Elev= 30
       0  462.21   62.18     458  127.64  451.11  150.55  449.58  186.55  449.35
  255.28   446.5     288  443.21  310.91  440.03  366.55  434.21  389.46  431.17
  513.83  426.67  520.37  425.94  526.92  424.13  540.01  422.94  549.83  424.45
  559.65   427.6  562.92  427.99  572.74  426.22  598.93  425.63  638.21   426.6
  785.51  426.71  821.52  428.48  847.71  431.13  880.44  436.66  926.27  442.57
  952.45  444.82 1014.65  448.61 1047.38  451.92 1112.85  457.22 1129.22     460
#Mann= 3 , 0 , 0
       0     .12       0  526.92    .045       0  549.83     .12       0
Bank Sta=526.92,549.83
XS Rating Curve= 0 ,0
Exp/Cntr=0.3,0.1

Type RM Length L Ch R = 1 ,13004.92,481.25,491.44,498.12
Node Name=981
XS GIS Cut Line= 3
2425084.24817595252397.7549709382425411.94535519252020.442405358
2425739.87941061251642.857202515
#Sta/Elev= 30
       0  454.13   58.79  448.61   71.86  446.64  127.39  443.11  163.32  439.98
  258.04  429.07  303.77  425.58   310.3  423.43  313.57  421.57  316.83  420.55
   329.9  420.13  333.17  420.38  336.43  422.12   339.7  424.55  346.23  425.62
  372.36  425.36  385.43  424.55  418.09  424.92  424.62   425.7  444.22  425.13
  483.42  425.79  503.02   425.1  623.96   425.7  663.18  428.59  705.68  429.56
  751.44  432.03  813.54  437.04  856.04  438.14  931.22  444.61  999.86  449.49
#Mann= 3 , 0 , 0
       0     .12       0  313.57    .045       0  336.43     .12       0
Bank Sta=313.57,336.43
XS Rating Curve= 0 ,0
Exp/Cntr=0.3,0.1

Type RM Length L Ch R = 1 ,12513.48,508.51,508.56,503.04
Node Name=982
XS GIS Cut Line= 3
2425202.45233586252755.482273847 2425647.0921946252484.571726441
2426076.20682195252192.759317935
#Sta/Elev= 30
       0   440.9  108.06  437.57  160.46  437.08  189.93  435.74   232.5  437.28
  383.13  437.39  415.88  434.07  445.35  429.49  468.28   424.9   491.2  424.19
  497.75  422.53  507.57  421.46  510.85  420.26  514.12  419.18  523.93  418.82
   527.2  420.32  530.46  423.36  533.73  424.26  546.78  425.25  579.42  422.69
  621.85  423.75  680.59  422.81  719.76  424.21  739.34  423.64   752.4  424.72
  765.45  424.25  791.56  426.24  847.04  426.76  948.22   432.4 1039.61  439.35
#Mann= 3 , 0 , 0
       0     .12       0  510.85    .045       0   527.2     .12       0
Bank Sta=510.85,527.2
XS Rating Curve= 0 ,0
Exp/Cntr=0.3,0.1

Type RM Length L Ch R = 1 ,12004.92,509.05,500,467.66
Node Name=983
XS GIS Cut Line= 3
2425580.25177711253145.0756547752425987.67451869252818.853538185
2426378.42045636252505.985069439
#Sta/Elev= 30
       0   466.8   75.03  468.66  117.44  467.76  150.06  466.48  198.99  462.43
  313.16  449.62  407.76  435.58  437.12  429.82  456.69  427.41  479.53  426.26
  505.62  421.25  512.15  418.65  515.41  416.85  521.93  416.35  528.48  417.92
  535.02   421.4  548.11  422.13  600.45  421.15  623.36  421.95  688.79  421.56
  705.15  422.59  724.78  422.35  737.87  423.72  809.84  425.17  839.29  428.56
  858.92  432.52  894.91  437.28  934.17  441.21   953.8  443.03  1022.5  445.85
#Mann= 3 , 0 , 0
       0     .12       0  512.15    .045       0  528.48     .12       0
Bank Sta=512.15,528.48
XS Rating Curve= 0 ,0
Exp/Cntr=0.3,0.1

Type RM Length L Ch R = 1 ,11504.92,527.56,544.83,553.95
Node Name=984
XS GIS Cut Line= 3
2426201.16293685253592.2817813612426332.00617911253106.993381858
2426472.36449419252586.412402019
#Sta/Elev= 30
       0  474.43   68.54  467.62  110.97  461.72  124.02  458.77  150.13  454.89
  248.05  443.27     297  438.81  352.49  435.97  394.91   432.3  427.55  428.47
  453.66  423.79  476.51  423.03  483.04  420.93  489.56  417.23  502.62  415.74
  505.89  416.73  509.15  418.89  512.42  420.42  515.69  420.79  574.51  419.93
  590.85  420.86  679.07  420.94  698.68  421.94  734.62  421.73  764.03  423.65
  786.91  423.44  822.85  424.77  940.49  437.15  989.51  440.96 1041.79  443.37
#Mann= 3 , 0 , 0
       0     .12       0  489.56    .045       0  509.15     .12       0
Bank Sta=489.56,509.15
XS Rating Curve= 0 ,0
Exp/Cntr=0.3,0.1

Type RM Length L Ch R = 1 ,10960.09,458.64,455.17,439.08
Node Name=985
XS GIS Cut Line= 3
2426559.40237786253549.1279962662426881.01000236253162.853506356
2427212.19437936252765.076414764
#Sta/Elev= 30
       0  445.67   26.11  444.32  101.18  435.53  130.55  433.45  179.51  426.74
  208.89   423.6  267.64  420.47  293.75  420.77   306.8  419.94  310.07  419.59
  319.21  415.59  329.65  414.07  336.18  414.67  339.65  415.72  345.97  419.33
  349.23  419.67  401.45  418.52  499.37  419.54  509.18  418.84  620.57  421.59
  627.12  420.94  646.77  421.73  663.15  421.44  669.71  422.12   725.4  421.94
  784.36  425.77  810.57  428.96  859.71  433.21   915.4  436.29 1020.23  444.68
#Mann= 3 , 0 , 0
       0     .12       0  319.21    .045       0  339.65     .12       0
Bank Sta=319.21,339.65
XS Rating Curve= 0 ,0
Exp/Cntr=0.3,0.1

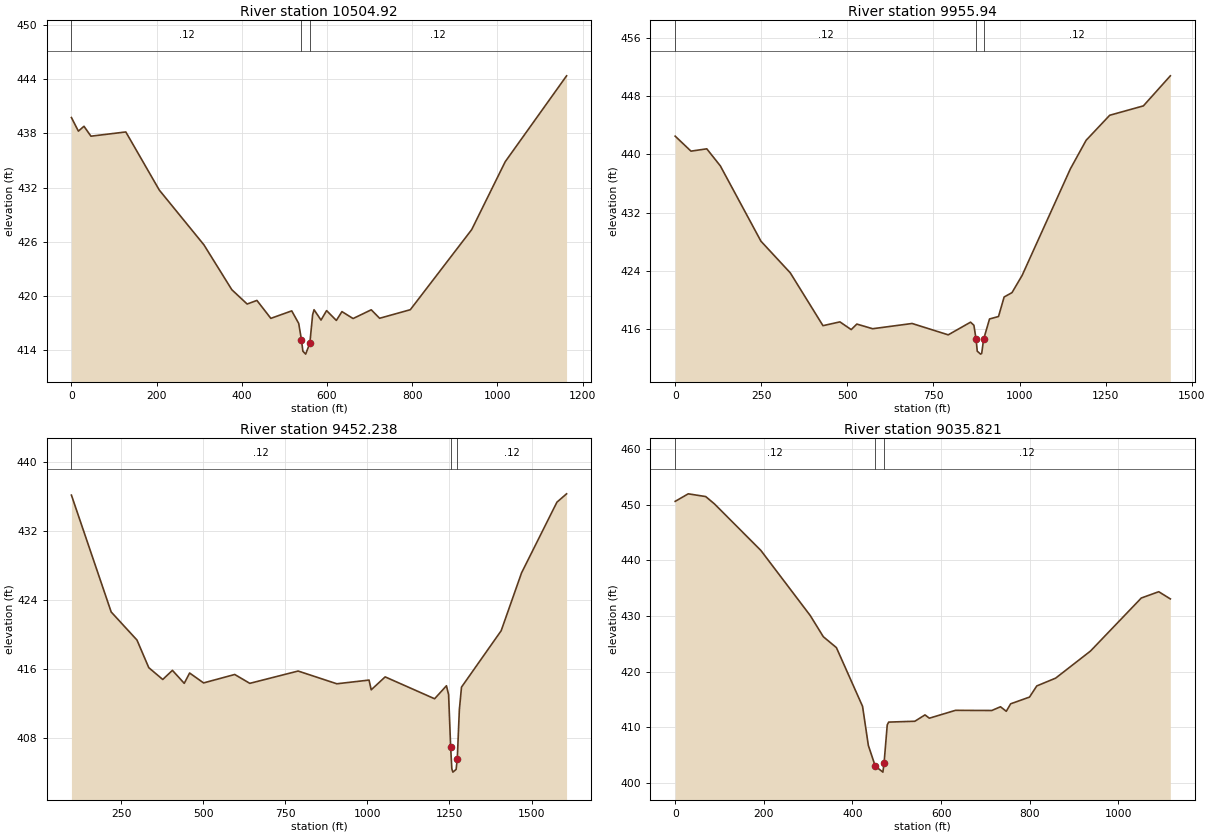
Type RM Length L Ch R = 1 ,10504.92,540.97,548.98,505.8
Node Name=986
XS GIS Cut Line= 4
2426671.55405644253660.6819070132427080.94136103253609.194149107
2427137.06952961253487.4420960252427402.02273986252931.515386358
#Sta/Elev= 30
       0  439.77   16.37  438.26   29.47   438.8   45.85   437.7  127.71  438.17
  206.31  431.72   311.1  425.64  376.59  420.66  412.61  419.07   435.5  419.47
   468.2  417.48  517.25  418.31   533.6  416.92  540.14  415.09  543.41  413.84
  549.96  413.51  559.78  414.73  566.33  417.88  569.61  418.44  585.99  417.29
  599.09  418.34  622.02  417.25  635.12  418.23  661.33  417.46  703.91  418.43
  723.57  417.49  795.64  418.44  939.77  427.33 1018.38  434.86 1162.52   444.4
#Mann= 3 , 0 , 0
       0     .12       0  540.14    .045       0  559.78     .12       0
Bank Sta=540.14,559.78
XS Rating Curve= 0 ,0
Exp/Cntr=0.3,0.1

Type RM Length L Ch R = 1 ,9955.94 ,494.18,503.7,491.6
Node Name=987
XS GIS Cut Line= 4
2426662.43924527253685.4213588542427461.81461503253610.907400265
 2427488.3641026253514.1520163572427609.88321653 252993.22228393
#Sta/Elev= 30
       0  442.51   45.88  440.45   91.75  440.77  131.08  438.43  249.04  428.08
  334.24  423.73  429.27  416.47  478.43  416.99   511.2  415.93  527.58  416.69
  573.46  416.05  688.15  416.77  793.01  415.21  857.86  416.95  867.57  416.52
  874.04  414.57  877.28  412.97  886.99  412.56  890.23  412.65  895.73  414.59
  912.96  417.39  939.05  417.73  955.36  420.41  978.19  421.01 1007.55  423.37
  1147.8  438.02 1193.46  441.94 1261.96  445.38 1359.81  446.67 1438.09   450.8
#Mann= 3 , 0 , 0
       0     .12       0  874.04    .045       0  895.73     .12       0
Bank Sta=874.04,895.73
XS Rating Curve= 0 ,0
Exp/Cntr=0.3,0.1

Type RM Length L Ch R = 1 ,9452.238,423.59,416.42,402.87
Node Name=988
XS GIS Cut Line= 4
 2426794.9430263253703.2143208922427885.37511961253782.639996439
2427906.99581127253713.7776013462428012.87685502253387.541449694
#Sta/Elev= 30
    98.2  436.15  219.32  422.58  297.88  419.32  333.89  416.11  376.44  414.74
   405.9   415.8  441.91  414.29  458.28  415.49  500.83  414.34  595.76  415.32
  641.59  414.29  788.89  415.72  906.74  414.24 1004.94  414.67 1011.49  413.54
 1054.04  415.04 1204.65   412.5 1240.74  414.01  1247.3  412.97 1253.56  406.86
 1257.14  404.36 1260.42  403.98 1270.23   404.3 1273.75  405.53 1280.03  411.22
 1286.57  413.85 1407.43   420.4  1469.5  427.12  1577.3  435.33 1606.69   436.3
#Mann= 3 , 0 , 0
    98.2     .12       0 1253.56    .045       0 1273.75     .12       0
Bank Sta=1253.56,1273.75
XS Rating Curve= 0 ,0
Exp/Cntr=0.3,0.1

Type RM Length L Ch R = 1 ,9035.821,487.11,489.12,479.03
Node Name=989
XS GIS Cut Line= 3
 2428250.9019476254375.7182065992428241.46003737 253874.37898618
2428229.86393194253258.638091683
#Sta/Elev= 30
       0  450.57    29.5  451.92   68.82  451.43   88.49  450.12  193.36  441.76
  304.79  430.07  334.29  426.27  363.78  424.32  422.77  413.78  435.88  406.75
  451.41  403.06  468.66  401.97  471.24  403.52  478.49  410.45  481.76  410.95
  540.74   411.1  563.67  412.24   573.5  411.65  632.46  413.06  714.35  413.03
  734.01   413.7  747.11  412.89  756.94  414.23  799.52  415.44   815.9  417.44
  858.49  418.84  937.11   423.7 1051.76  433.22 1091.07  434.35 1117.28  433.06
#Mann= 3 , 0 , 0
       0     .12       0  451.41    .045       0  471.24     .12       0
Bank Sta=451.41,471.24
XS Rating Curve= 0 ,0
Exp/Cntr=0.3,0.1