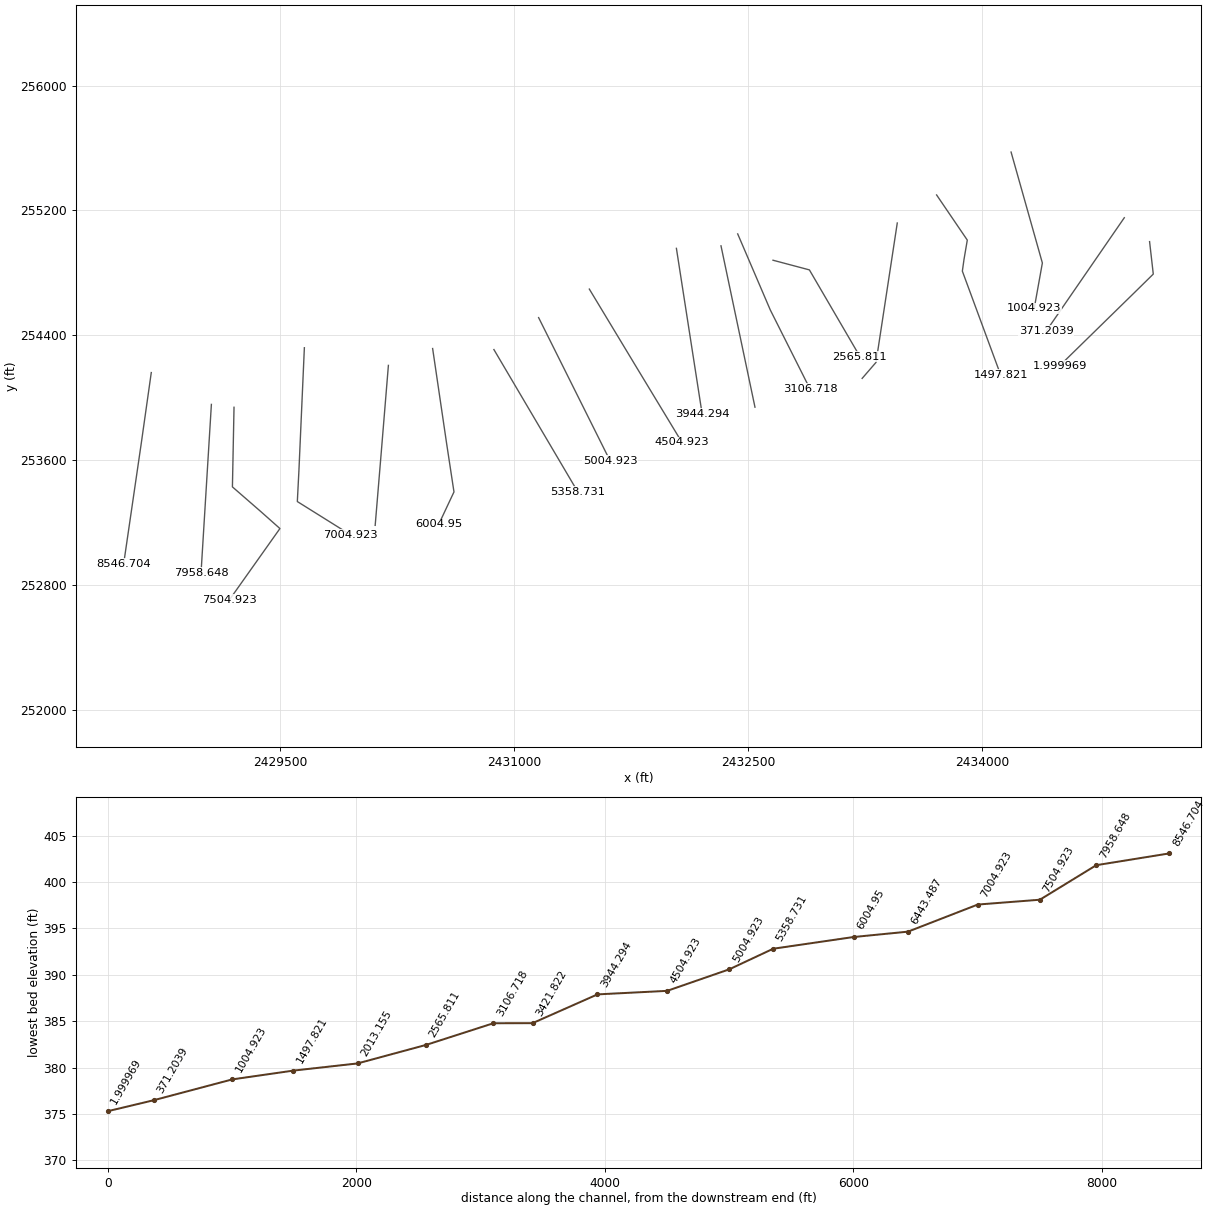
HEC-RAS study LongMarshRun.prj: Long Marsh Run

--- LongMarshRun.g01 (geometry) --- (continued)

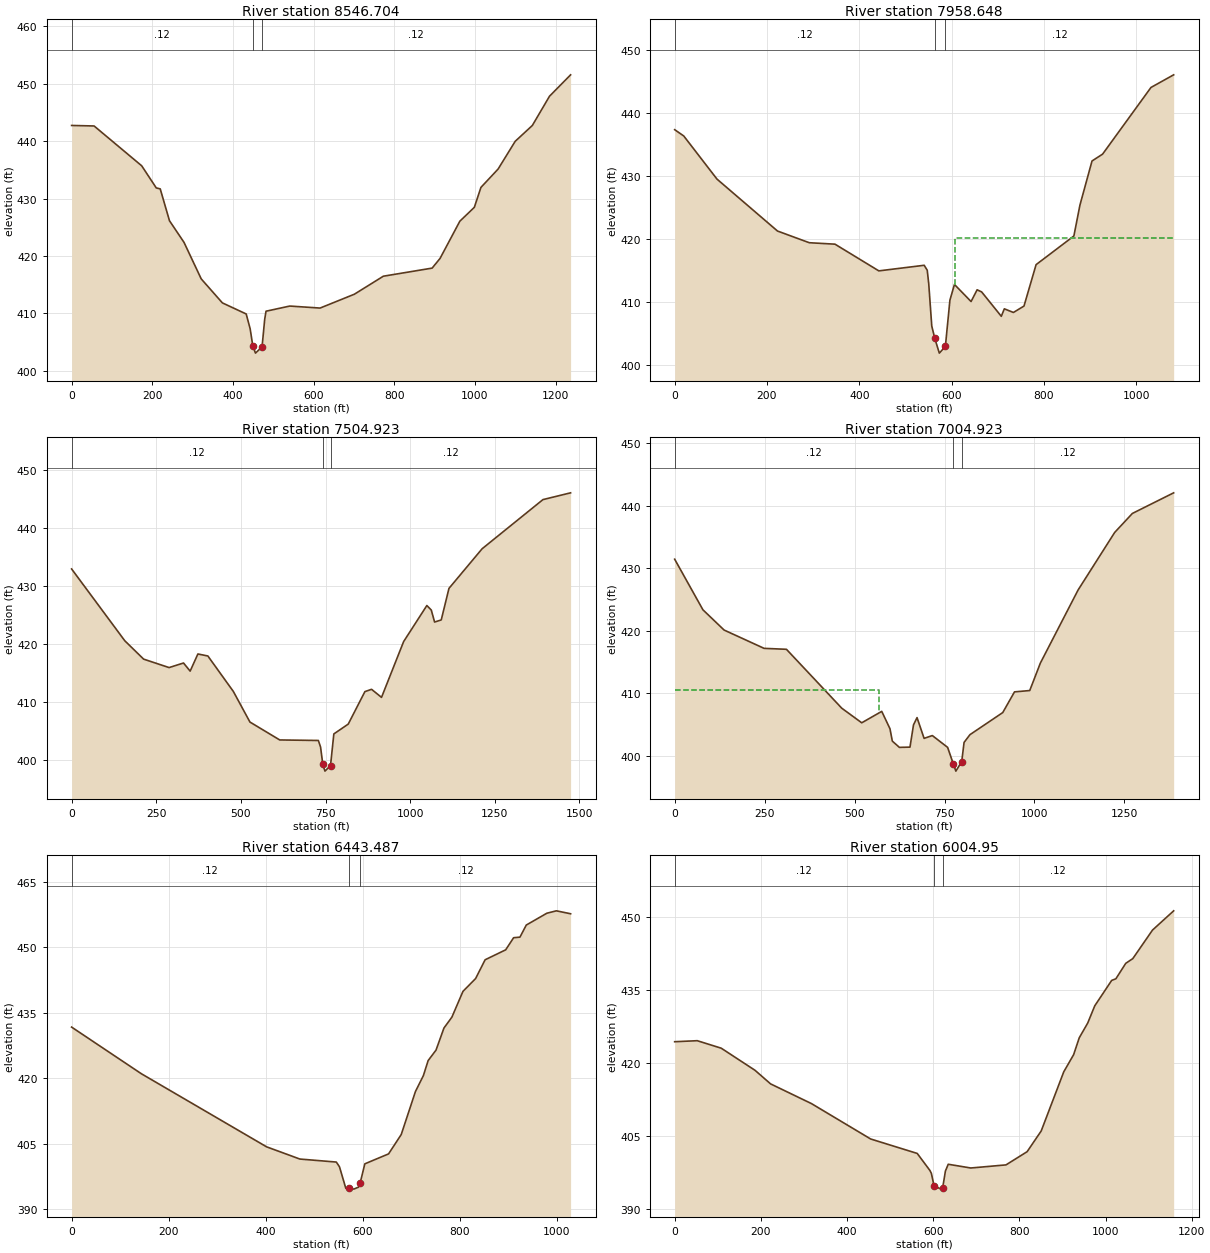
Type RM Length L Ch R = 1 ,8546.704,578,588.06,587.17
Node Name=990
XS GIS Cut Line= 3
2428675.85221319254160.4548576032428611.52130511  253705.8652156
2428499.08583444252935.924498275
#Sta/Elev= 30
       0  442.74   55.75  442.65  173.81  435.71  209.88  431.86  219.72  431.69
  242.68  426.14  278.75  422.37  321.38  416.01  373.85  411.83  432.88   409.9
  442.72  407.31  449.28  404.34  455.84  403.08   472.2  404.17  478.74  408.96
     482  410.38  540.85  411.28  616.05  410.93  701.05  413.34  772.98  416.48
  893.94  417.89  913.56  419.58   962.6  426.06  998.56  428.48 1014.91  431.95
 1057.41  435.14 1099.91  439.98 1142.41  442.74 1184.91  447.83 1237.22  451.56
#Mann= 3 , 0 , 0
       0     .12       0  449.28    .045       0   472.2     .12       0
Bank Sta=449.28,472.2
XS Rating Curve= 0 ,0
Exp/Cntr=0.3,0.1

Type RM Length L Ch R = 1 ,7958.648,399.54,453.73,465.21
Node Name=991
XS GIS Cut Line= 3
2429061.11620644253956.4237696082429025.52736686 253377.44822152
2428994.77316327252877.122450516
#Sta/Elev= 30
       0  437.37   19.66  436.37   91.76   429.5  222.85  421.24  291.67  419.38
  347.39  419.15  442.42   414.9  540.74  415.79   547.3     415  550.57  412.86
  557.13  406.12  563.68  404.16  573.51  401.81  586.62  402.87  596.45  410.23
  606.28  412.74  642.32  410.02  655.42  411.89  665.25  411.55  707.84  407.67
  714.39  408.86  734.05  408.28  756.99   409.3   783.2  415.89   865.1  420.45
  878.21  425.36  904.42  432.39  927.35  433.48 1032.19  444.09 1081.34   446.1
#Mann= 3 , 0 , 0
       0     .12       0  563.68    .045       0  586.62     .12       0
#XS Ineff= 2 , 0
                          607.95          420.07
Permanent Ineff=
       F       F
Bank Sta=563.68,586.62
XS Rating Curve= 0 ,0
Exp/Cntr=0.3,0.1

Type RM Length L Ch R = 1 ,7504.923,516.35,500,453.66
Node Name=992
XS GIS Cut Line= 5
2429206.15823919253938.0327302662429195.89382403253427.641690686
2429377.90986419253269.4031620172429500.39091845253160.667159021
2429177.44766669252704.985327601
#Sta/Elev= 30
       0  432.98  157.08  420.59  212.71  417.42  287.97  415.96  330.51  416.75
  350.15  415.35  373.05  418.31  402.51  417.96  477.77  411.84  526.79  406.56
  614.79  403.47  728.86  403.38  735.38  402.25  742.04  399.24  748.42  398.09
  764.78  399.05  774.61  404.51  817.19  406.21  866.33  411.81  885.98  412.21
  915.46  410.82  980.78  420.45 1049.37  426.67 1062.44  425.89 1072.24  423.82
 1091.83  424.18  1114.7  429.63 1212.68  436.47 1392.32  444.95 1473.97  446.12
#Mann= 3 , 0 , 0
       0     .12       0  742.04    .045       0  764.78     .12       0
Bank Sta=742.04,764.78
XS Rating Curve= 0 ,0
Exp/Cntr=0.3,0.1

Type RM Length L Ch R = 1 ,7004.923,559.68,561.44,554.62
Node Name=993
XS GIS Cut Line= 4
2429657.04841353254319.5687126072429622.27584527253535.529598266
2429611.92809694 253333.730461182429951.10228735253121.652145192
#Sta/Elev= 30
       0  431.47   78.48  423.38  137.34  420.14  248.52  417.21  310.65  417.06
  464.35  407.64  519.94   405.3  575.53  407.13  598.42  404.35  604.96  402.37
  624.58  401.37  654.01  401.41  663.82  404.97  673.63  406.13  693.25  402.81
  716.14  403.26  758.65  401.37  774.81  398.67  781.54  397.57  797.85  399.11
  804.36  402.16  820.66   403.4  911.92  406.94  944.51  410.25  986.87  410.46
 1016.38  414.85 1121.31  426.55 1222.95  435.75 1272.14  438.79  1386.9  442.09
#Mann= 3 , 0 , 0
       0     .12       0  774.81    .045       0  797.85     .12       0
#XS Ineff= 2 , 0
          566.56   410.5
Permanent Ineff=
       F       F
Bank Sta=774.81,797.85
XS Rating Curve= 0 ,0
Exp/Cntr=0.3,0.1

Type RM Length L Ch R = 1 ,6443.487,428.92,438.54,442.12
Node Name=994
XS GIS Cut Line= 3
2430195.58998735254206.4609991912430148.77708887253636.512335941
2430110.91135094253181.183850273
#Sta/Elev= 30
       0  431.76  143.78  421.08  401.94  404.34  470.57  401.54  545.73  400.85
  552.26  399.77  565.33  394.84  571.87  395.02  581.66  394.65  591.45   395.1
  595.04   396.1   604.5  400.44  653.46  402.72  679.57  407.15  708.94  417.02
  725.26  420.65  735.05  424.09  751.36   426.5  767.68  431.55     784  434.03
  806.84  439.94  832.95  442.88  852.54  447.18  894.96  449.46  911.28  452.23
  924.33  452.36  937.39  455.13  979.81  457.84   999.4  458.39 1028.77  457.72
#Mann= 3 , 0 , 0
       0     .12       0  571.87    .045       0  595.04     .12       0
Bank Sta=571.87,595.04
XS Rating Curve= 0 ,0
Exp/Cntr=0.3,0.1

Type RM Length L Ch R = 1 ,6004.95 ,630.18,646.22,650.65
Node Name=995
XS GIS Cut Line= 4
2430479.10352795254314.4817805142430568.26509503253708.965275019
2430615.86703394253395.4160333572430518.50666437253188.232064515
#Sta/Elev= 30
       0  424.42   52.37  424.63  108.01  423.09  186.56  418.53  222.56  415.74
  317.48  411.68  454.94  404.39  562.95  401.42  592.41  397.91  595.68  397.34
  602.02  394.75  618.58  394.07  622.07  394.38  628.39   397.8  634.93  399.19
  687.24  398.42  768.98  399.06  818.02  401.78  850.72  406.05  903.03  418.22
  925.92  421.75     939  425.23  958.62  428.26  974.97  431.81 1014.22  437.04
 1024.03  437.38 1046.92  440.56 1063.27  441.53 1109.05  447.41 1158.11  451.37
#Mann= 3 , 0 , 0
       0     .12       0  602.02    .045       0  622.07     .12       0
Bank Sta=602.02,622.07
XS Rating Curve= 0 ,0
Exp/Cntr=0.3,0.1

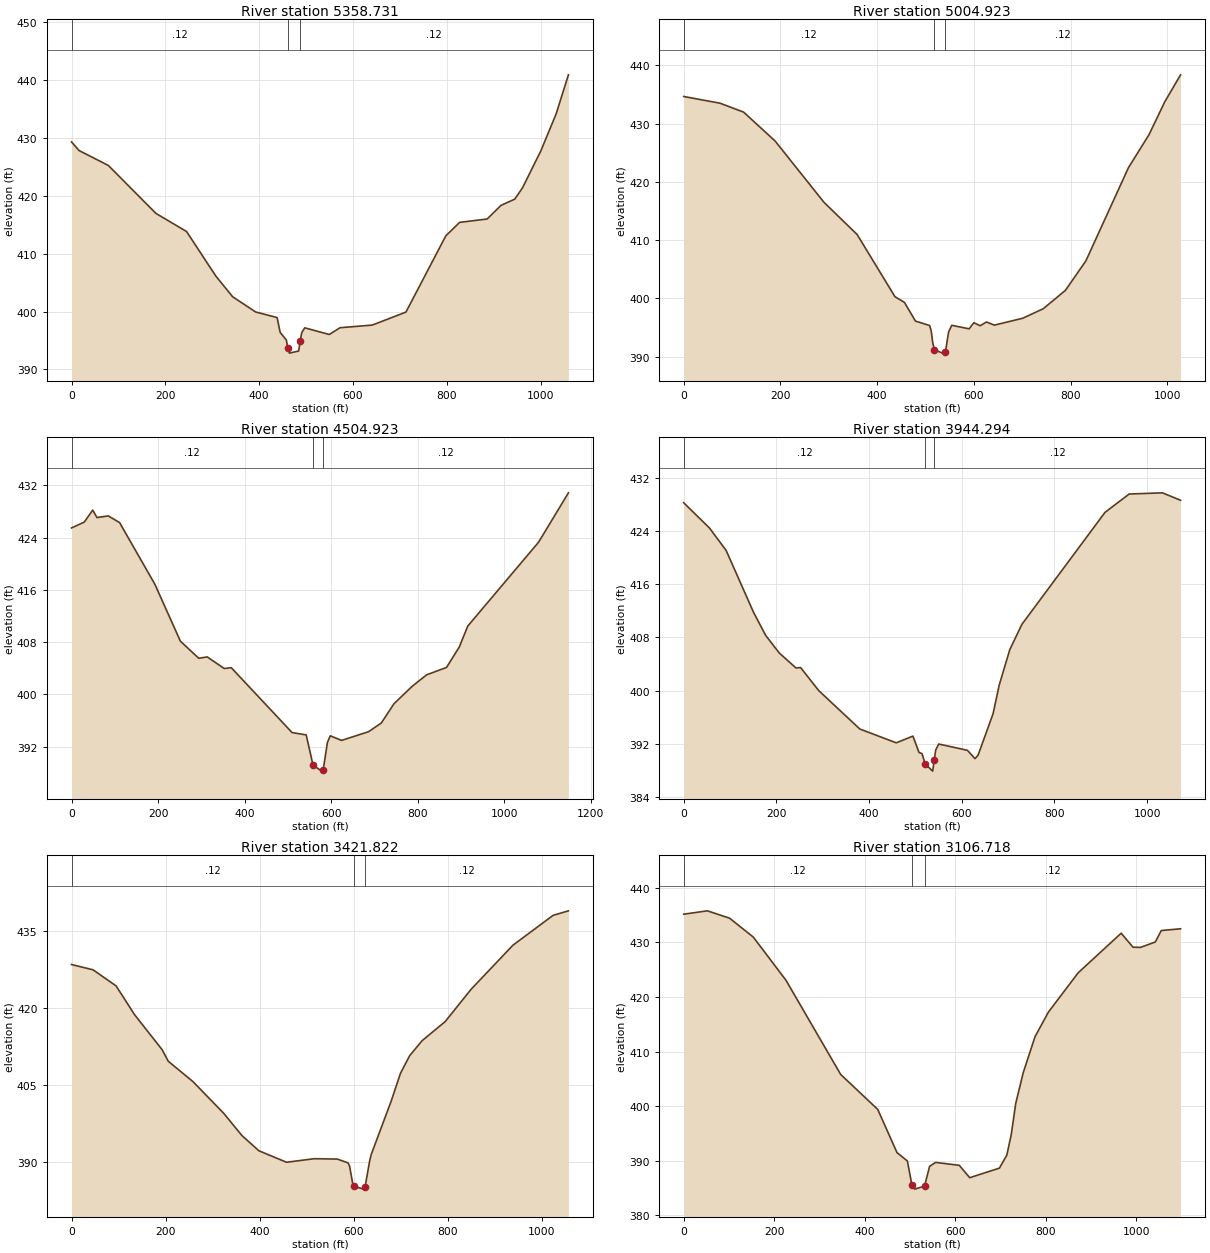
Type RM Length L Ch R = 1 ,5358.731,352.09,353.81,345.5
Node Name=996
XS GIS Cut Line= 3
2430871.85700752254307.835468352 2431154.3272431253828.695022434
2431409.93237494253395.124367267
#Sta/Elev= 30
       0  429.29   16.36  427.79   78.52  425.23  179.95  416.95  245.38  413.81
  307.55  406.14  343.54  402.55  392.62  399.92  438.42  398.95  444.96  396.38
  458.05  395.08  461.32  393.67   464.6  392.81  484.23  393.17  487.75  394.85
  490.77  396.33  497.31  397.18  549.66  396.03  572.55   397.2  641.18  397.65
  713.08   399.9  798.05  413.06  827.47  415.39   886.3  415.98  915.71  418.33
  945.12  419.41  961.47  421.34 1000.68  427.74 1033.37  434.14 1059.51  440.88
#Mann= 3 , 0 , 0
       0     .12       0  461.32    .045       0  487.75     .12       0
Bank Sta=461.32,487.75
XS Rating Curve= 0 ,0
Exp/Cntr=0.3,0.1

Type RM Length L Ch R = 1 ,5004.923,471.78,500,491.12
Node Name=997
XS GIS Cut Line= 3
2431158.41745803254512.4987729342431394.31134319254039.867172271
2431617.24101545253593.210257187
#Sta/Elev= 30
       0  434.66      75  433.51  123.91  431.98  189.12  427.01   290.2  416.48
  358.67  410.96  436.93  400.28  456.49   399.3  479.32  396.09  508.67  395.33
  511.93  394.35  515.19  392.28   518.4  391.21  534.75  390.59  541.28  390.81
  547.81  394.22  554.33  395.37  590.22  394.76  600.01  395.81  613.06  395.29
  626.11  395.94  642.43   395.4  701.16  396.58  743.57  398.22  789.25  401.36
  831.67  406.43  919.76  422.45  962.18   428.1   994.8  433.75 1027.43  438.38
#Mann= 3 , 0 , 0
       0     .12       0   518.4    .045       0  541.28     .12       0
Bank Sta=518.4,541.28
XS Rating Curve= 0 ,0
Exp/Cntr=0.3,0.1

Type RM Length L Ch R = 1 ,4504.923,560.18,560.63,539.05
Node Name=998
XS GIS Cut Line= 3
2431483.37875035254695.4616616072431776.98643085254208.842228025
2432077.10033195253712.971500605
#Sta/Elev= 30
       0  425.47    29.4  426.36   48.99   428.2   58.79  427.06   84.92  427.31
  111.05  426.29  192.71  416.84   251.5  408.15  293.97  405.53  313.56  405.74
  352.76  403.97  369.09  404.09  509.54  394.17   542.2  393.81  558.02  389.18
  578.15  388.27  581.43  388.47  591.26  392.68  597.81  393.67     624  392.97
  686.22   394.3   715.7  395.63  745.17  398.59  787.74  401.29  820.49     403
  866.33  404.13   895.8  407.25  915.45  410.46 1079.19   423.3 1147.95  430.84
#Mann= 3 , 0 , 0
       0     .12       0  558.02    .045       0  581.43     .12       0
Bank Sta=558.02,581.43
XS Rating Curve= 0 ,0
Exp/Cntr=0.3,0.1

Type RM Length L Ch R = 1 ,3944.294,485.87,522.47,405.63
Node Name=999
XS GIS Cut Line= 3
2432041.47638744254956.5621892662432124.51788802254422.293900847
2432206.18012628253896.898626193
#Sta/Elev= 30
       0  428.28   55.71  424.48   91.75  421.09  150.74   411.8  176.95  408.32
  206.44  405.66  242.49  403.41  252.32  403.48  291.64     400  380.12  394.23
  458.76  392.15  494.81  393.16  507.91   390.7  514.47  390.53  521.02  388.99
  537.41  387.89  540.68  389.56  543.95  391.07  550.47  391.97  612.45  391.02
  628.76  389.77  635.28  390.27   667.9  396.56  680.95  400.83  703.78  406.16
  729.88  409.97  909.29  426.83  961.48  429.59 1033.24  429.77 1072.39  428.65
#Mann= 3 , 0 , 0
       0     .12       0  521.02    .045       0  540.68     .12       0
Bank Sta=521.02,540.68
XS Rating Curve= 0 ,0
Exp/Cntr=0.3,0.1

Type RM Length L Ch R = 1 ,3421.822,299.98,315.1,314.98
Node Name=1000
XS GIS Cut Line= 3
2432327.27634078254972.6717371052432437.68884961 254448.46379602
 2432545.0905377253938.552086189
#Sta/Elev= 30
       0  428.51   45.73  427.48   94.73  424.36  133.93  418.77  192.72  411.93
  205.79  409.68  258.06  405.74  323.39  399.58  362.58  395.21  398.52  392.26
  457.31  390.02  516.11  390.71  565.21  390.64  588.15   389.9  591.43  389.26
  597.98  385.91  601.26  385.36  620.92  384.79   624.2  385.13  634.03  390.25
  637.31   391.5  679.91  401.93  699.58  407.32  719.24  410.77  745.46  413.67
  794.62  417.39  850.34  423.74  938.83  432.27 1024.04  438.07 1056.81  438.96
#Mann= 3 , 0 , 0
       0     .12       0  601.26    .045       0   624.2     .12       0
Bank Sta=601.26,624.2
XS Rating Curve= 0 ,0
Exp/Cntr=0.3,0.1

Type RM Length L Ch R = 1 ,3106.718,527.61,540.91,514.5
Node Name=1001
XS GIS Cut Line= 3
2432434.28400077255049.138775766 2432643.1060897254561.932401106
2432897.87756178254054.984924182
#Sta/Elev= 30
       0  435.16   52.35  435.78  101.43  434.43  153.79  430.97  225.77  423.08
  346.84  405.79  428.64  399.39  471.18  391.47  494.08  389.94   503.9  385.62
  510.44  384.78   531.9  385.33  543.19  388.95  556.31  389.68  608.78  389.14
  631.74  386.87  697.33  388.63  713.73  391.01  723.57  394.81  733.41  400.49
   749.8  406.08  776.04  412.72  805.56  417.22  871.15  424.41  966.26  431.68
  992.49  429.11 1008.89  429.08 1041.69  430.07  1054.8  432.17 1097.44  432.49
#Mann= 3 , 0 , 0
       0     .12       0   503.9    .045       0   531.9     .12       0
Bank Sta=503.9,531.9
XS Rating Curve= 0 ,0
Exp/Cntr=0.3,0.1

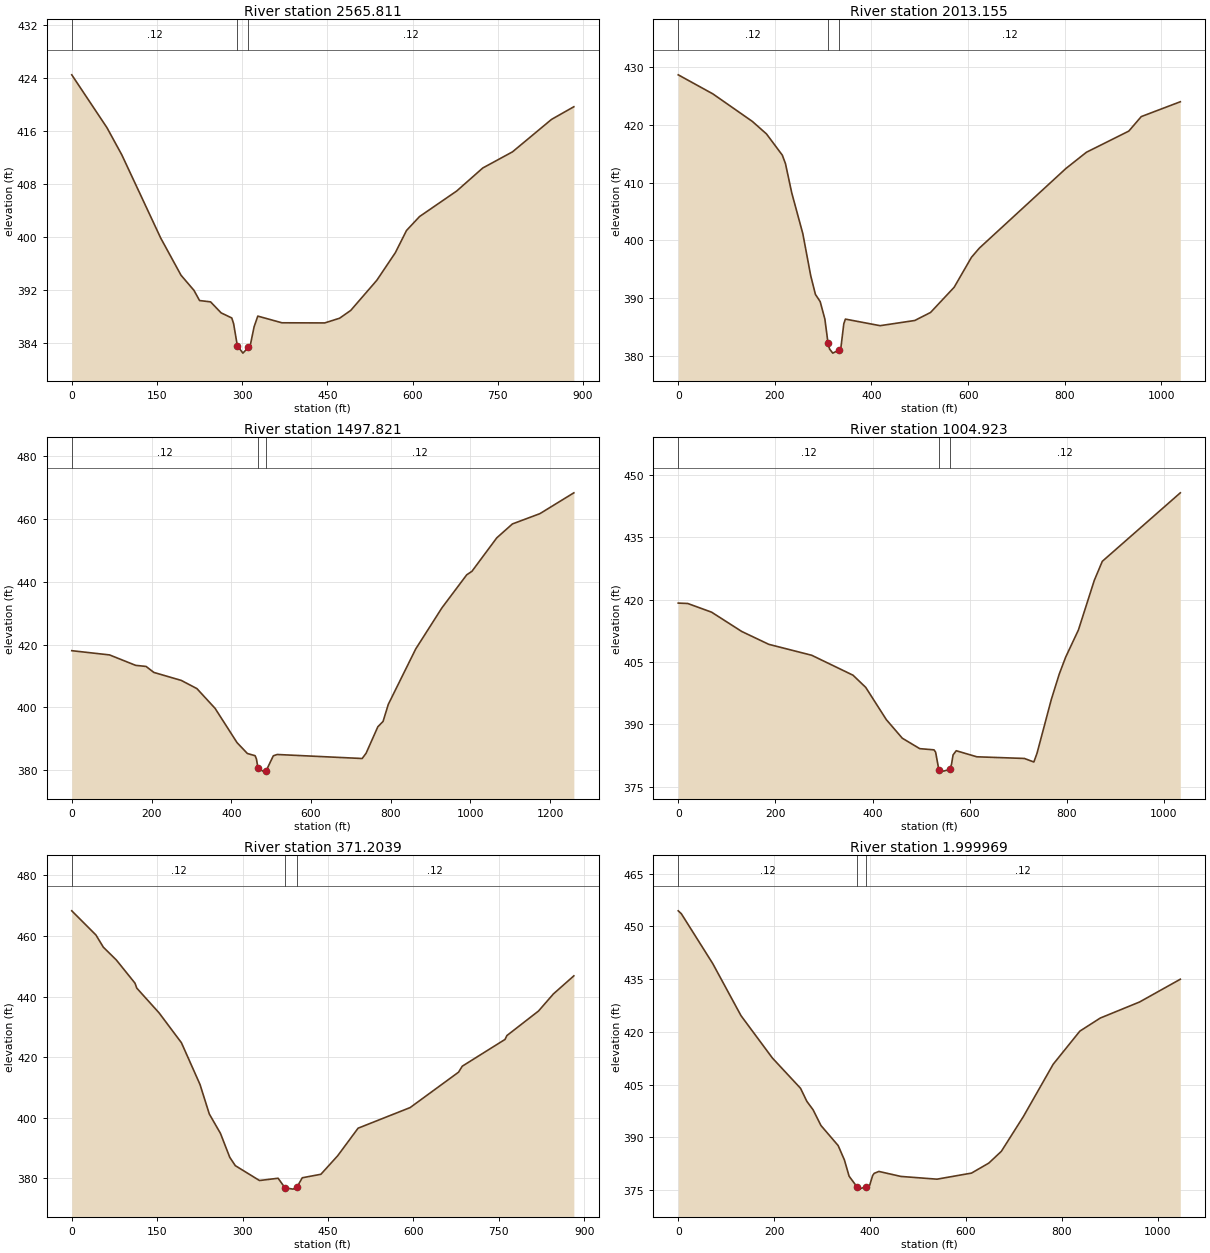
Type RM Length L Ch R = 1 ,2565.811,571.52,552.66,530.82
Node Name=1002
XS GIS Cut Line= 4
2432660.63295752254880.4015804382432893.85624436 254818.45977518
2432912.55633819254786.3975033462433217.66104294254263.284376353
#Sta/Elev= 30
       0  424.47   61.96  416.49   88.05   412.4  156.52  399.84  192.39  394.21
  215.22  391.92     225  390.39   244.4  390.19  262.96  388.53   281.7  387.76
  284.97   386.9  291.52  383.56  301.34  382.45  311.16  383.33  314.43  383.68
  320.98  386.41  327.53  388.04  370.08  387.03  445.37  387.01  471.56  387.72
   491.2   388.9  537.03  393.44  569.76  397.62   589.4  400.97  612.32  403.07
  677.79  406.93  723.61   410.4  775.99  412.84  844.73  417.74  884.01  419.65
#Mann= 3 , 0 , 0
       0     .12       0  291.52    .045       0  311.16     .12       0
Bank Sta=291.52,311.16
XS Rating Curve= 0 ,0
Exp/Cntr=0.3,0.1

Type RM Length L Ch R = 1 ,2013.155,514.11,515.33,512.41
Node Name=1003
XS GIS Cut Line= 4
2433457.05656153 255118.944082352433381.29096502254621.994288847
2433320.87901236254225.7496745142433232.04848136254123.127832517
#Sta/Elev= 30
       0  428.71   71.81   425.4  153.42  420.63   182.8  418.45  215.44  414.78
  221.97  413.31  235.02  408.22  257.87  401.17   274.2  393.89  283.99  390.63
  293.78  389.39  303.57  386.34   310.1  382.14  313.37  381.14   319.9  380.45
  332.95  380.99  336.22  381.07  342.74  385.55  346.01  386.35  417.82  385.21
  489.64  386.11  522.24   387.5  571.13  391.87  606.97  397.07  623.27  398.66
  802.49  412.47  844.86  415.28   932.6  418.95  958.45  421.47 1039.24  424.04
#Mann= 3 , 0 , 0
       0     .12       0   310.1    .045       0  332.95     .12       0
Bank Sta=310.1,332.95
XS Rating Curve= 0 ,0
Exp/Cntr=0.3,0.1

Type RM Length L Ch R = 1 ,1497.821,477.35,492.9,503.8
Node Name=1004
XS GIS Cut Line= 5
2433709.14168727255298.7334209382433905.85750119255009.453815773
2433884.66627061 254885.043303432433874.17350945254810.451917186
2434119.29801919254146.389597014
#Sta/Elev= 30
       0  418.05   94.81   416.7   160.2  413.38  186.36  413.03  205.97  411.12
  274.63  408.58  313.86  405.97  359.54  399.66  414.55  388.75  440.44   385.3
  459.85  384.59  463.09  383.56  467.05  380.74  479.31  379.68  487.48  379.79
  505.51  384.57  515.33  384.98  728.32   383.7  738.15  385.37  767.65  393.81
  780.76  395.52  793.86  400.95  862.68  418.61  928.23  431.67  990.49  442.21
  1003.6  443.33 1065.87  453.99 1105.19  458.43 1174.01   461.7 1259.22  468.34
#Mann= 3 , 0 , 0
       0     .12       0  467.05    .045       0  487.48     .12       0
Bank Sta=467.05,487.48
XS Rating Curve= 0 ,0
Exp/Cntr=0.3,0.1

Type RM Length L Ch R = 1 ,1004.923,645.73,633.72,591.46
Node Name=1005
XS GIS Cut Line= 4
2434186.47537827 255573.648553522434333.91602828255051.030504271
2434386.99630269254862.7109990272434334.91307352 254572.34642227
#Sta/Elev= 30
       0  419.18   19.63  419.08    68.7  416.99  130.85  412.34  186.46  409.25
  274.78  406.62  359.83  401.82     386  398.89  428.53  391.11  461.24  386.66
  497.22  384.14  526.66  383.85  529.93  383.28  536.48   379.1  546.28  378.73
  559.32  379.16  562.58  380.35  565.84  382.63  572.37  383.64  614.76  382.18
  712.59  381.78  732.15  380.93  738.68  383.04  768.17  396.01  784.56  402.14
  797.68  406.18   823.9  412.71  856.67  424.68  873.06  429.23 1033.67  445.72
#Mann= 3 , 0 , 0
       0     .12       0  536.48    .045       0  559.32     .12       0
Bank Sta=536.48,559.32
XS Rating Curve= 0 ,0
Exp/Cntr=0.3,0.1

Type RM Length L Ch R = 1 ,371.2039,361.66,369.2,350.74
Node Name=1006
XS GIS Cut Line= 3
2434912.13665661255152.7996576882434754.78264061254924.344077855
2434412.06252553254426.762723938
#Sta/Elev= 30
       0  468.33   42.43  460.36   55.48  456.32   78.33  452.09  110.96  444.47
  114.22  442.81  153.39  434.63  192.55   424.8  225.19  411.01   241.5  401.28
  261.08  394.88   277.4  386.99   287.2  384.22  329.66  379.32  362.32  380.07
  374.44   376.9  388.44  376.48  395.08  377.05  404.77  380.23  437.43  381.38
  466.82  387.47  502.75  396.59  594.19   403.4  679.11  415.07  685.64  417.05
  760.76  425.89  764.02  427.16  819.54  435.26  845.67   440.9  881.59  446.87
#Mann= 3 , 0 , 0
       0     .12       0  374.44    .045       0  395.08     .12       0
Bank Sta=374.44,395.08
XS Rating Curve= 0 ,0
Exp/Cntr=0.3,0.1

Type RM Length L Ch R = 1 ,1.999969,13.38,2,2.34
Node Name=1007
XS GIS Cut Line= 4
2435074.17439027254999.690383852 2435097.8429781254791.582204267
2434974.35897312254670.2110559342434499.08761394254205.419334605
#Sta/Elev= 30
       0  454.43    6.55  453.59      72  439.43  130.91  424.63  196.36  412.59
  255.19  403.96  268.25  400.27  281.32  397.86  297.66   393.4  333.59  387.69
  346.66   383.6  356.46  378.97  373.04  375.93  376.06   375.3  392.17  375.97
  398.97  376.23  405.52  379.16  408.79  379.79  418.62  380.33  464.46  378.91
  539.78  378.13  611.82  379.86  647.85   382.7  674.04  386.05  719.89  395.91
  782.11   410.8  837.78  420.22  880.35  423.94  962.22   428.5 1047.36  434.98
#Mann= 3 , 0 , 0
       0     .12       0  373.04    .045       0  392.17     .12       0
Bank Sta=373.04,392.17
XS Rating Curve= 0 ,0
Exp/Cntr=0.3,0.1

Chan Stop Cuts=-1
Use User Specified Reach Order=0
Composite Channel Slope=5